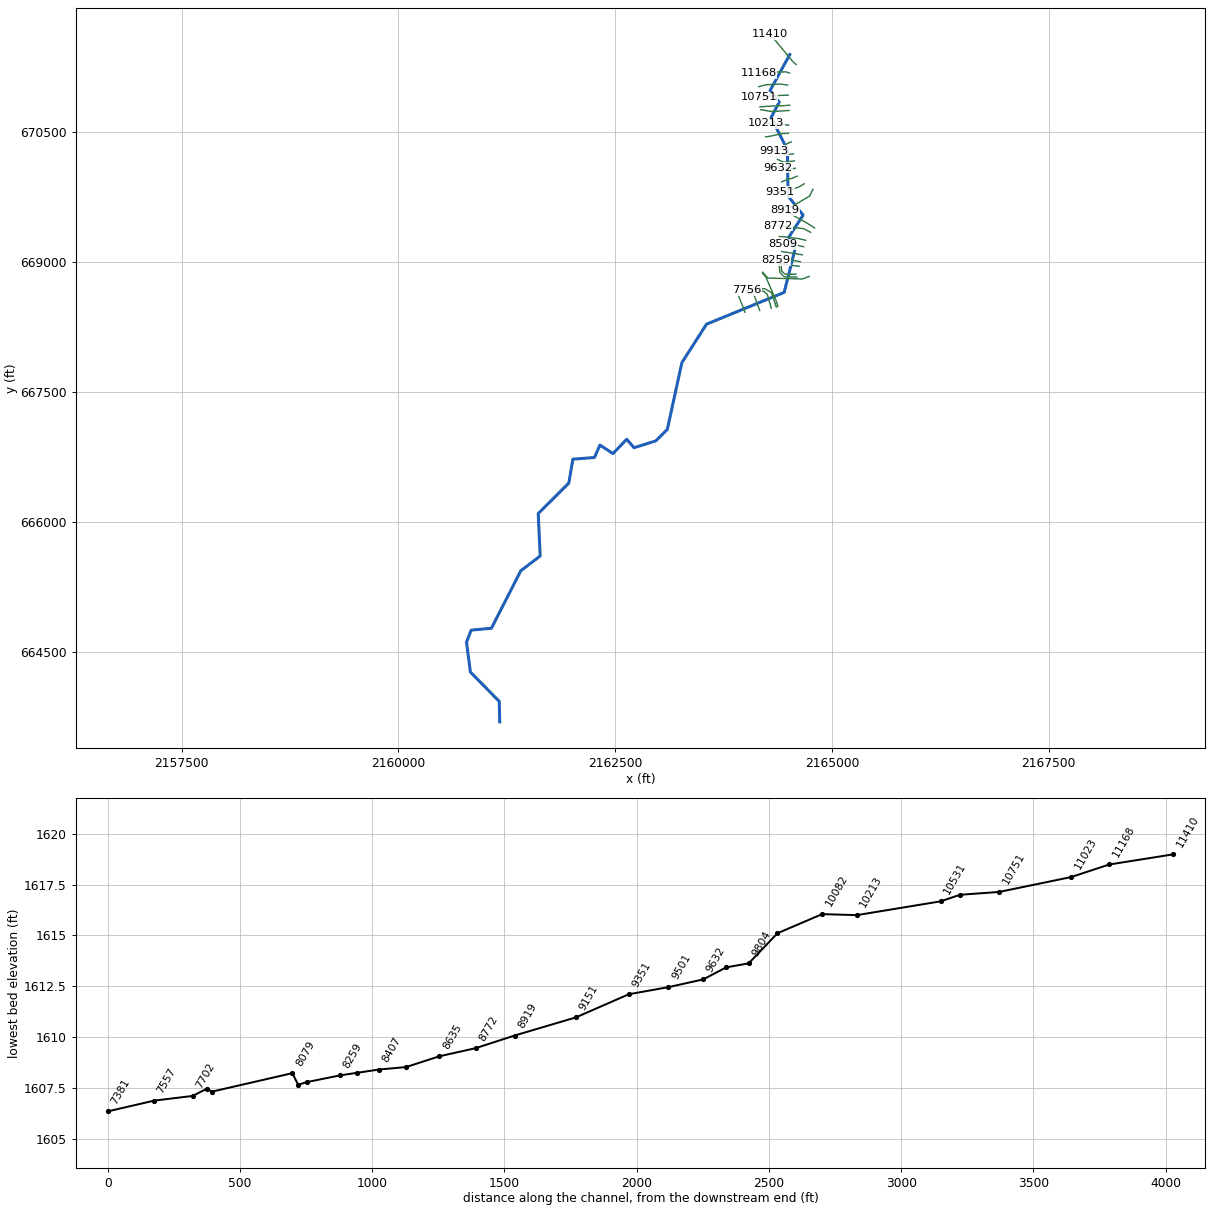
--- KANAWHARN.prj (project) ---

Proj Title=KANAWHARN
Current Plan=p01
Default Exp/Contr=0,0
English Units
Geom File=g01
Flow File=f01
Plan File=p01
BEGIN DESCRIPTION:
---------- MODELED AS PART OF WVEMD CTP PROGRAM, 2023----------
Stream Name: Kanawha Run
Flood Zone:  AFH
Upshur County, WV
HEC-RAS Version: RAS 6.3
Vertical Datum: NAVD88
Projection: NAD 1983 StatePlane West Virginia S FIPS 4702 (US Feet)
Terrain: 1-meter LIDAR (FEMA Region III 3DEP collected 2016-2018)
Land Use: 2019 NLCD
Hydrologic Method:
WV SIR2010-5033 regression equations
Additional Model Notes:
None
END DESCRIPTION:
DSS Export Rating Curves= 0
DSS Export Rating Curve Sorted= 0
DSS Export Volume Flow Curves= 0
DXF OffsetX= 0
DXF OffsetY= 0
DXF ScaleX= 0
DXF ScaleY= 0

--- KANAWHARN.p01 (plan) ---

Plan Title=Floodplain
Program Version=6.30
Short Identifier=Floodplain
Geom File=g01
Flow File=f01
Subcritical Flow
K Sum by GR= 0
Std Step Tol= 0.01
Critical Tol= 0.01
Num of Std Step Trials= 20
Max Error Tol= 0.3
Flow Tol Ratio= 0.001
Split Flow NTrial= 30
Split Flow Tol= 0.02
Split Flow Ratio= 0.02
Log Output Level= 0
Friction Slope Method= 1
Unsteady Friction Slope Method= 2
Unsteady Bridges Friction Slope Method= 1
Parabolic Critical Depth
Global Vel Dist= 0 , 0 , 0
Global Log Level= 0
CheckData=False
Encroach Param=-1 ,0,0, 0
Mapping Interval=1HOUR
Computation Time Step Use Courant=        0
Computation Time Step Use Time Series=    0
Computation Time Step Count To Double=0
Computation Time Step Max Doubling=0
Computation Time Step Max Halving=0
Computation Time Step Residence Courant=0
Run HTab= 0
Run UNet= 0
Run Sediment= 0
Run PostProcess= 0
Run WQNet= 0
Run RASMapper=-1
UNET Theta= 0
UNET Theta Warmup= 0
UNET ZTol= 0
UNET ZSATol= 0
UNET MxIter= 0
UNET Max Iter WO Improvement= 0
UNET MaxInSteps= 0
UNET DtIC= 0
UNET DtMin= 0
UNET MaxCRTS= 0
UNET WFStab= 0
UNET SFStab= 0
UNET WFX= 1
UNET SFX= 1
UNET Gravity=32.17405
UNET 1D Methodology=Finite Difference
UNET DSS MLevel= 1
UNET Pardiso=0
UNET DZMax Abort= 0
UNET Use Existing IB Tables= 0
UNET Froude Reduction=False
UNET Froude Limit= 0
UNET Froude Power= 0
UNET D1 Cores= 0
UNET WindReference=Eulerian
UNET WindDragFormulation=Hsu (1988)
UNET D2 Coriolis=0
UNET D2 Cores= 0
UNET D2 Theta= 1
UNET D2 Theta Warmup= 1
UNET D2 Z Tol= 0.01
UNET D2 Volume Tol= 0.01
UNET D2 Max Iterations= 20
UNET D2 Equation= 0
UNET D2 RampUpFraction=0.1
UNET D2 TimeSlices= 1
UNET D2 Turbulence Formulation=Non-Conservative (original)
UNET D2 Eddy Viscosity=0.3
UNET D2 Transverse Eddy Viscosity=0.1
UNET D2 Smagorinsky Mixing=0
UNET D2 BCVolumeCheck=0
UNET D2 Cores=0
UNET D2 SolverType=PARDISO (Direct)
UNET D2 Minimum Iterations= 3
UNET D2 Maximum Iterations= 30
UNET D2 Restart Number= 10
UNET D2 Relaxation Coeff=1.3
UNET D2 SOR Precondition Iterations= 10
UNET D2 ILUT Maximum Fill= 8
UNET D2 ILUT Tolerance=1E-08
UNET D2 Convergence Tolerance=0.00001
UNET D1D2 MaxIter= 0
UNET D1D2 ZTol=0.01
UNET D1D2 QTol=0.1
UNET D1D2 MinQTol=1
Write IC File= 0
Write IC File at Fixed DateTime=0
Write IC File at Sim End=0
Echo Input=False
Echo Parameters=False
Echo Output=False
Write Detailed= 0
HDF Write Warmup=0
HDF Write Time Slices=0
HDF Flush=0
HDF Compression= 1
HDF Chunk Size= 1
HDF Spatial Parts= 1
HDF Use Max Rows=0
HDF Fixed Rows= 1
Calibration Method= 0
Calibration Iterations= 20
Calibration Max Change=0.05
Calibration Tolerance=0.2
Calibration Maximum=1.5
Calibration Minimum=0.5
Calibration Optimization Method= 1
WQ AD Non Conservative
WQ ULTIMATE=-1
WQ Max Comp Step=1HOUR
WQ Output Interval=15MIN
WQ Output Selected Increments= 0
WQ Output face flow=0
WQ Output face velocity=0
WQ Output face area=0
WQ Output face dispersion=0
WQ Output cell volume=0
WQ Output cell surface area=0
WQ Output cell continuity=0
WQ Output cumulative cell continuity=0
WQ Output face conc=0
WQ Output face dconc_dx=0
WQ Output face courant=0
WQ Output face peclet=0
WQ Output face adv mass=0
WQ Output face disp mass=0
WQ Output cell mass=0
WQ Output cell source sink temp=0
WQ Output nsm pathways=0
WQ Output nsm derived pathways=0
WQ Create Restart=0
WQ Fixed Restart=0
WQ System Summary=0
WQ Write To DSS=0
Sorting and Armoring Iterations= 10
XS Update Threshold= 0.02
Bed Roughness Predictor= 0
Hydraulics Update Threshold= 0.02
Energy Slope Method= 1
Volume Change Method= 1
Sediment Retention Method= 0
Sediment TS Multiplier= 1
Warm Up Method= 0
XS Weighting Method= 0
Number of US Weighted Cross Sections= 1
Number of DS Weighted Cross Sections= 1
Upstream XS Weight=0
Main XS Weight=1
Downstream XS Weight=0
Number of DS XS's Weighted with US Boundary= 1
Upstream Boundary Weight= 1
Weight of XSs Associated with US Boundary= 0
Number of US XS's Weighted with DS Boundary= 1
Downstream Boundary Weight= 0.5
Weight of XSs Associated with DS Boundary= 0.5
Percentile Method= 0
Sediment Output Level= 3
Mass or Volume Output= 0
Output Increment Type= 1
Profile and TS Output Increment= 1
Transport Output Increment 1
XS Output Flag= 0
XS Output Increment= 10
Read HDF5 Sediment Hotstart= 0
Sediment Hotstart Type= 0
Write Gradation File= 0
Read Gradation Hotstart= 0
Write HDF5 File= 1
Write Binary Output= 1
Write DSS Sediment File= 0
DSS Sediment Output Type= 1
SV Curve= 0
Specific Gage Flag= 0
Subcell Erosion Methods= 0
Subcell Deposition Methods= 0
Advection Scheme= 1
Matrix Solver= 0
Implicit Weighting Factor= 1
Maximum Outer Loop Convergence Iterations= 5
Convergence Maximum Absolute= 0.001
Convergence RMSE= 0.0001
Grain Fractions Max Abs Error= 0.001
Max Subgrid Regions= 1
Max Subgrid Length Scale= 3.402823E+38
Initial Layer Thickness= 3.402823E+38
Min Layer Thickness= 3.402823E+38
Max Layer Thickness= 3.402823E+38
Number of Layers= 5

--- KANAWHARN.f01 (steady flow) ---

Flow Title=Flows
Program Version=6.31
Number of Profiles= 1
Profile Names=01pct
River Rch & RM=KANAWHARN,Main            ,11410
     790
River Rch & RM=KANAWHARN,Main            ,8101
    1220
River Rch & RM=KANAWHARN,Main            ,6209
    1460
Boundary for River Rch & Prof#=KANAWHARN,Main            , 1
Up Type= 0
Dn Type= 3
Dn Slope=0.00414
DSS Import GetInterval= 0
DSS Import GetPeak= 0
DSS Import FillOption= 0

--- KANAWHARN.g01 (geometry) ---

Geom Title=Geometry
Program Version=6.31

River Reach=KANAWHARN       ,Main
Reach XY= 30
2164514.63127213671388.811478692     2164286.255      670973.506
     2164392.393      670839.753     2164298.588      670661.816
     2164486.998      670289.202     2164493.924      669757.051
      2164667.74       669537.02     2164503.281      669282.306
     2164575.452      669147.351     2164449.253      668644.933
     2163554.104      668278.586     2163269.343      667834.431
     2163101.565      667064.335     2162968.613      666932.127
     2162717.848      666853.747     2162632.628      666951.157
     2162475.467      666786.184     2162324.773      666883.709
     2162260.586       666740.34     2162012.682      666721.711
     2161965.294      666445.678     2161612.568      666093.038
     2161635.404      665604.814      2161412.11      665434.947
     2161072.749      664771.304     2160839.096      664749.441
     2160785.411      664610.594     2160830.454      664265.252
     2161162.947      663927.722     2161168.671      663690.749

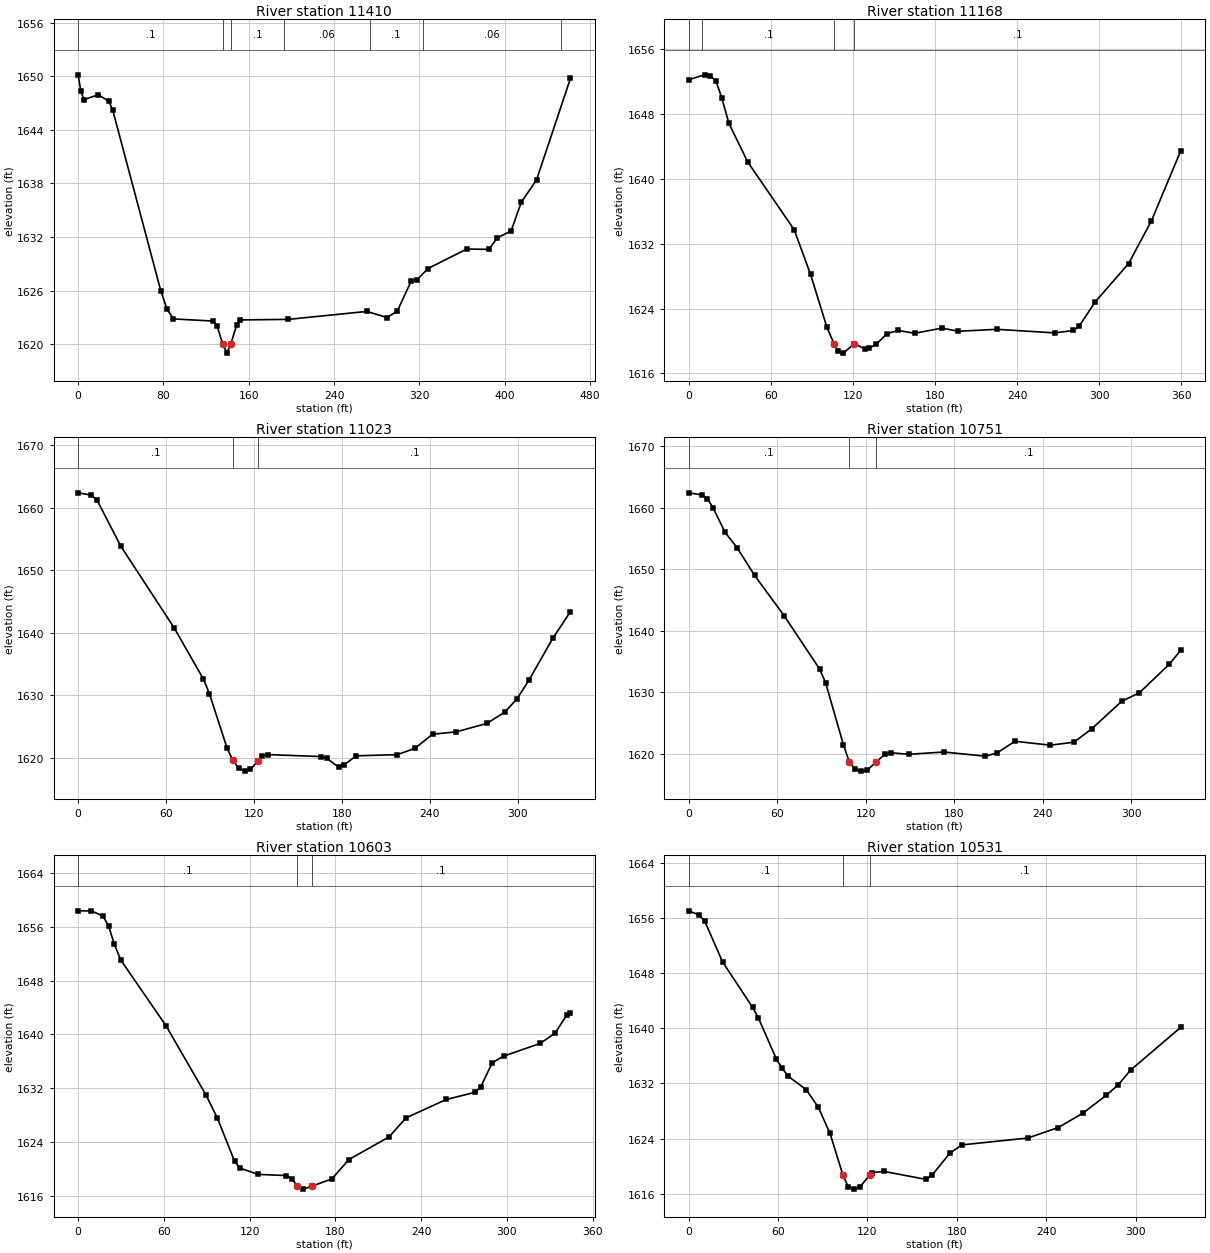
Type RM Length L Ch R = 1 ,11410   ,242.5,242.5,242.5
XS GIS Cut Line= 3
2164586.00122784 671273.382976012164547.30697647671309.927546746
2164286.18112108671623.945615309
#Sta/Elev= 30
       0 1650.16     2.5 1648.33     5.5 1647.39      19 1647.93    28.8 1647.19
    32.3 1646.26    77.6 1625.93    83.3 1623.92    89.4 1622.82   126.9 1622.58
   130.3 1622.03   135.5 1620.04   139.5 1618.99     143 1619.97   148.6 1622.12
     152 1622.71   196.9 1622.77   270.7 1623.66   289.6 1622.98   299.2 1623.68
   312.4 1627.08   317.6 1627.18     328 1628.46   364.4 1630.65   385.2 1630.61
   392.9 1631.89     406 1632.68   415.6 1635.91   429.8 1638.38   461.6 1649.75
#Mann= 7 ,-1,0
       0      .1       0   135.5    .045       0     143      .1       0
  193.22     .06       0  273.22      .1       0  323.22     .06       0
  453.22      .1       0
Bank Sta=135.5,143
XS Rating Curve= 0 ,0
Exp/Cntr(USF)=0,0
Exp/Cntr=0.3,0.1

Type RM Length L Ch R = 1 ,11168   ,144.3,144.9,145.9
XS GIS Cut Line= 4
2164511.38004101671175.458919063 2164470.0967367671188.237084683
2164199.78938706671186.2712130492164155.34854133 671174.49766696
#Sta/Elev= 30
       0 1652.26    11.7 1652.87    15.9 1652.74    20.1 1652.09    24.3    1650
    29.5 1646.87    43.2 1642.11    77.1 1633.75    89.1 1628.22   101.1 1621.66
   106.5 1619.57   109.1 1618.77   113.1 1618.49   121.1 1619.67   129.1 1618.97
   131.6 1619.07   137.1  1619.6   145.1 1620.91   153.1 1621.29   165.1 1620.94
   185.1 1621.58   197.1 1621.19   225.1 1621.43   267.7 1620.99   281.1 1621.29
   285.1 1621.79   297.1 1624.84   321.4 1629.56     338 1634.82   359.5  1643.5
#Mann= 4 ,-1,0
       0     .06       0      10      .1       0   106.5    .045       0
   121.1      .1       0
Bank Sta=106.5,121.1
XS Rating Curve= 0 ,0
Exp/Cntr(USF)=0,0
Exp/Cntr=0.3,0.1

Type RM Length L Ch R = 1 ,11023   ,266.4,272,266.3
XS GIS Cut Line= 4
2164488.99943036671036.4628791492164400.19612347671048.071154559
2164238.84109527671039.9453617722164157.11233135671017.586196795
#Sta/Elev= 30
       0 1662.37     8.9 1662.01    12.9 1661.19    29.1 1653.84    65.4 1640.82
    85.5 1632.58    89.6 1630.24   101.6 1621.56   105.6 1619.59   109.6 1618.35
   113.6 1617.87   117.6 1618.15   122.8 1619.53   125.6 1620.32   129.6 1620.51
   165.7  1620.2   169.7  1619.9   177.7 1618.52   181.7  1618.9   189.7 1620.32
   217.7  1620.5   229.8 1621.51   241.8 1623.77     258 1624.15   278.8 1625.49
   291.2 1627.31   299.5 1629.44   307.6 1632.41   323.9 1639.12   335.9 1643.35
#Mann= 3 ,-1,0
       0      .1       0   105.6    .045       0   122.8      .1       0
Bank Sta=105.6,122.8
XS Rating Curve= 0 ,0
Exp/Cntr(USF)=0,0
Exp/Cntr=0.3,0.1

Type RM Length L Ch R = 1 ,10751   ,147.2,148,145.4
XS GIS Cut Line= 4
2164496.92409482670920.8434373052164416.66935124670917.260636252
2164223.91465462670905.7956728842164164.44015714670897.196950358
#Sta/Elev= 30
       0 1662.42     8.8  1662.1    12.8 1661.48    16.8 1659.88    24.8 1655.98
    32.8 1653.52    44.8 1648.97    64.8 1642.41    88.8 1633.75    92.9  1631.5
   104.9 1621.45   108.9 1618.62   112.9 1617.45   116.9 1617.14   120.9 1617.26
  126.84 1618.57   132.9 1619.86   136.9 1620.13   149.1 1619.88     173 1620.25
     201 1619.57   209.1 1620.11   221.1    1622   245.1 1621.36   261.1 1621.85
   273.2 1624.03   293.4 1628.49   305.5  1629.9   325.7 1634.53   333.5 1636.82
#Mann= 3 ,-1,0
       0      .1       0   108.9    .045       0  126.84      .1       0
Bank Sta=108.9,126.84
XS Rating Curve= 0 ,0
Exp/Cntr(USF)=0,0
Exp/Cntr=0.3,0.1

Type RM Length L Ch R = 1 ,10603   ,71.7,72.1,72.2
XS GIS Cut Line= 4
2164513.40497966670804.0441229922164438.16615756670798.311641307
2164288.40507356670793.2957198342164169.45607862670785.413557518
#Sta/Elev= 30
       0 1658.39     9.3 1658.37    17.3 1657.62    21.3 1656.15    25.3 1653.41
    29.9 1651.05    61.4 1641.33    89.5 1630.99    97.5 1627.53   109.5 1621.12
   113.3 1620.12     126 1619.19   145.5 1619.02   149.5 1618.58   153.5 1617.42
   157.5    1617   163.7 1617.45   177.5 1618.51   189.5  1621.4   217.5 1624.76
   229.5  1627.6   257.6 1630.33   277.6 1631.39   281.7 1632.18   289.8 1635.78
   297.7 1636.78   323.4 1638.67   333.8 1640.21   341.8 1642.84   344.5 1643.26
#Mann= 3 ,-1,0
       0      .1       0   153.5    .045       0   163.7      .1       0
Bank Sta=153.5,163.7
XS Rating Curve= 0 ,0
Exp/Cntr(USF)=0,0
Exp/Cntr=0.3,0.1

Type RM Length L Ch R = 1 ,10531   ,315.1,317.5,312.7
XS GIS Cut Line= 3
2164506.94567006670743.148136639 2164309.2499269670730.837412706
2164178.90108526670751.838059415
#Sta/Elev= 30
       0 1657.04     6.8 1656.47    10.8 1655.57    22.8 1649.64    42.9 1643.06
    46.9 1641.47    58.9 1635.55    62.9 1634.18    66.9 1633.04    78.9 1631.11
    86.9  1628.6    94.9 1624.75   103.4  1618.8     107 1617.04     111 1616.68
     115 1617.01   121.4  1618.7     123 1619.08     131 1619.25   159.1  1618.1
   163.1 1618.66   175.1 1621.85   183.1 1623.09   227.5 1624.09   247.8  1625.6
   264.2 1627.66   280.2  1630.3   288.3 1631.84   296.4 1633.94   330.1 1640.15
#Mann= 3 ,-1,0
       0      .1       0   103.4    .045       0   121.4      .1       0
Bank Sta=103.4,121.4
XS Rating Curve= 0 ,0
Exp/Cntr(USF)=0,0
Exp/Cntr=0.3,0.1

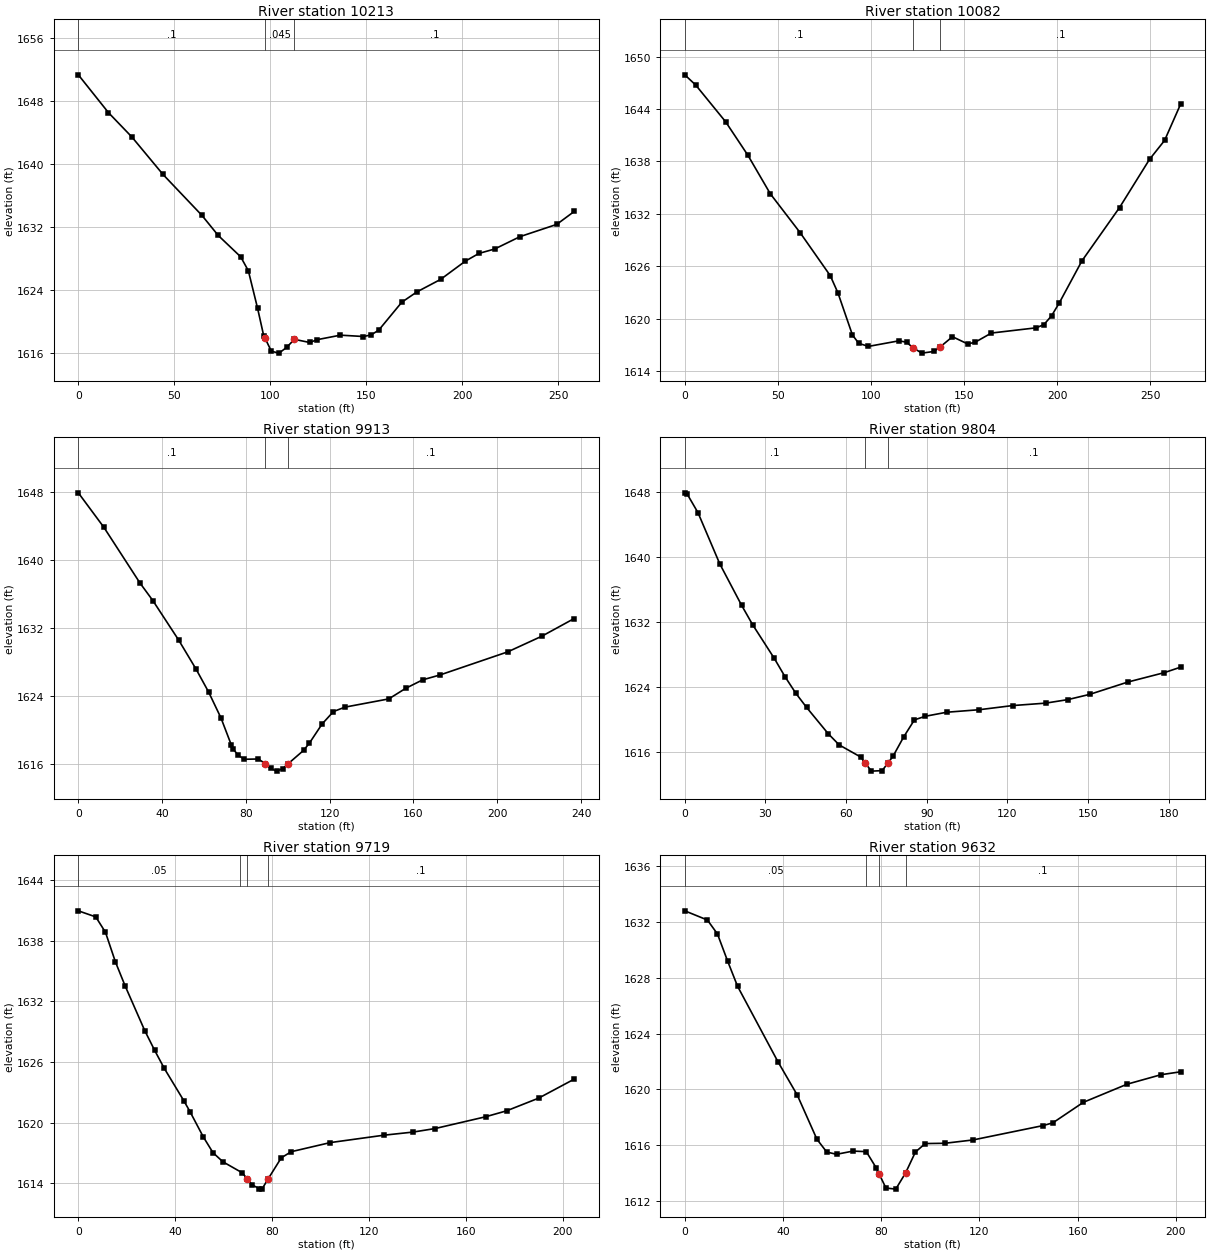
Type RM Length L Ch R = 1 ,10213   ,128.9,130.8,132.2
XS GIS Cut Line= 4
2164499.69472392670572.8913299182164419.19228052670586.160963446
2164328.95877253670584.3916789762164243.14847571670595.892028033
#Sta/Elev= 30
       0 1651.33    15.7 1646.53    27.9 1643.44    44.1 1638.69    64.4 1633.49
    72.9 1630.94    84.6 1628.23    88.6 1626.46    93.4 1621.71    96.6 1618.21
    97.3  1617.9   100.6 1616.24   104.6    1616   108.6 1616.74   112.6 1617.75
   120.6 1617.35   124.5 1617.71   136.6 1618.28   148.6 1618.11   152.6 1618.31
   156.6 1618.93   168.6 1622.47   176.5 1623.78   188.8 1625.36   201.7 1627.68
   208.8 1628.66     217 1629.22   230.2 1630.79   249.3 1632.34   258.4 1633.98
#Mann= 3 ,-1,0
       0      .1       0    97.3    .045       0   112.6      .1       0
Bank Sta=97.3,112.6
XS Rating Curve= 0 ,0
Exp/Cntr(USF)=0,0
Exp/Cntr=0.3,0.1

Type RM Length L Ch R = 1 ,10082   ,163.7,169.1,172.8
XS GIS Cut Line= 4
2164498.06460255670479.8965977632164427.29322373670476.947790312
2164293.61395263670447.4597158062164235.62073944670439.596229271
#Sta/Elev= 30
       0 1647.92     5.9 1646.74    21.9 1642.55    33.9  1638.7    45.9  1634.3
    61.9 1629.85    78.1 1624.92    82.2 1622.96      90 1618.13    93.4 1617.17
    98.6 1616.82     115 1617.46   119.1  1617.3   122.5 1616.66   127.3 1616.05
   133.7 1616.24     137 1616.74   143.7 1617.93   151.9  1617.1   155.9  1617.3
   164.6 1618.35   188.7 1618.95   192.8 1619.32   196.9 1620.32     201 1621.78
   213.2 1626.61   233.4 1632.72   249.5 1638.24   257.6 1640.41   266.2 1644.57
#Mann= 3 ,-1,0
       0      .1       0   122.5    .045       0     137      .1       0
Bank Sta=122.5,137
XS Rating Curve= 0 ,0
Exp/Cntr(USF)=0,0
Exp/Cntr=0.3,0.1

Type RM Length L Ch R = 1 ,9913    ,114.4,108.8,102.9
XS GIS Cut Line= 4
 2164531.4601503670380.2074899152164485.26216691670361.531709394
2164414.49078809670296.6579454792164325.04362875670280.930972409
#Sta/Elev= 30
       0 1647.94    12.2 1643.87    29.4 1637.31    35.6 1635.22    47.9 1630.57
    56.3  1627.1    62.2 1624.44    68.1 1621.38      73 1618.22      74 1617.69
    76.3 1616.99    79.2 1616.51    85.9 1616.54    89.3 1615.99    91.8 1615.43
    94.7 1615.11    97.7 1615.42   100.1 1615.97   107.5 1617.55   110.3 1618.41
   116.4 1620.68   121.8 1622.14   127.3 1622.66   148.2 1623.63   156.3 1624.88
   164.4 1625.88   172.6 1626.45     205 1629.18   221.3 1631.03   236.7 1633.11
#Mann= 3 ,-1,0
       0      .1       0    89.3    .045       0   100.1      .1       0
Bank Sta=89.3,100.1
XS Rating Curve= 0 ,0
Exp/Cntr(USF)=0,0
Exp/Cntr=0.3,0.1

Type RM Length L Ch R = 1 ,9804    ,84.7,85.4,85.9
XS GIS Cut Line= 4
2164557.01648154670243.5794113682164520.64785631670237.681796466
2164452.82528495670233.7500531992164375.17335542670251.442897903
#Sta/Elev= 30
       0 1647.89      .9 1647.73     4.9 1645.45      13 1639.15    21.1 1634.06
    25.2 1631.67    33.3  1627.5    37.3 1625.24    41.3 1623.21    45.3 1621.47
    53.3 1618.25    57.4 1616.86    65.4 1615.37    67.21614.587    69.4 1613.63
    73.4 1613.69    75.51614.609    77.4 1615.44    81.4 1617.84    85.4 1619.94
    89.4 1620.38    97.4 1620.88   109.5 1621.19   121.9  1621.7   134.2    1622
   142.4 1622.43   150.6 1623.08   164.8  1624.6   178.4 1625.76   184.4 1626.43
#Mann= 3 ,-1,0
       0      .1       0    67.2    .045       0    75.5      .1       0
Bank Sta=67.2,75.5
XS Rating Curve= 0 ,0
Exp/Cntr(USF)=0,0
Exp/Cntr=0.3,0.1

Type RM Length L Ch R = 1 ,9719    ,87,86.6,85.8
XS GIS Cut Line= 4
2164567.30299167670161.9593501822164540.76372462670158.027606914
2164445.41895038670146.2323771122164370.71582829670179.652194886
#Sta/Elev= 29
       0 1640.94     7.2 1640.34    11.2 1638.82    15.3  1635.9    19.3 1633.53
    27.4 1629.11    31.5 1627.15    35.5 1625.36    43.5 1622.19    46.1 1621.09
    51.6 1618.59    55.6 1617.03    59.7 1616.13    67.7 1615.04    69.81614.425
    71.8 1613.84    74.7 1613.48    75.8 1613.43    78.3 1614.42    83.8 1616.53
    87.9 1617.13     104 1618.03   126.1 1618.76   138.2 1619.07   147.3 1619.42
   168.1 1620.58   176.8 1621.17     190 1622.42   204.7  1624.3
#Mann= 4 ,-1,0
       0     .05       0   66.83      .1       0    69.8    .045       0
    78.3      .1       0
Bank Sta=69.8,78.3
XS Rating Curve= 0 ,0
Exp/Cntr(USF)=0,0
Exp/Cntr=0.3,0.1

Type RM Length L Ch R = 1 ,9632    ,129.3,131.4,130
XS GIS Cut Line= 4
2164577.14211238670076.9276310032164544.23265159670069.405468537
2164418.70656544670063.7638466882164381.09575312670083.509523161
#Sta/Elev= 27
       0 1632.81     9.2 1632.15    13.3 1631.15    17.4 1629.22    21.5 1627.39
    37.9 1621.99    45.8 1619.59    53.8 1616.42    57.8  1615.5    61.8 1615.34
    68.5 1615.57    73.9 1615.53    77.9 1614.38    79.21613.906    81.9 1612.92
    85.9 1612.84    89.9    1614    93.9  1615.5    97.9 1616.11   105.9 1616.13
   117.4 1616.37   145.9  1617.4   149.9  1617.6   162.3 1619.07   180.1 1620.37
   193.9 1621.05   201.9 1621.26
#Mann= 4 ,-1,0
       0     .05       0   73.76      .1       0    79.2    .045       0
    89.9      .1       0
Bank Sta=79.2,89.9
XS Rating Curve= 0 ,0
Exp/Cntr(USF)=0,0
Exp/Cntr=0.3,0.1

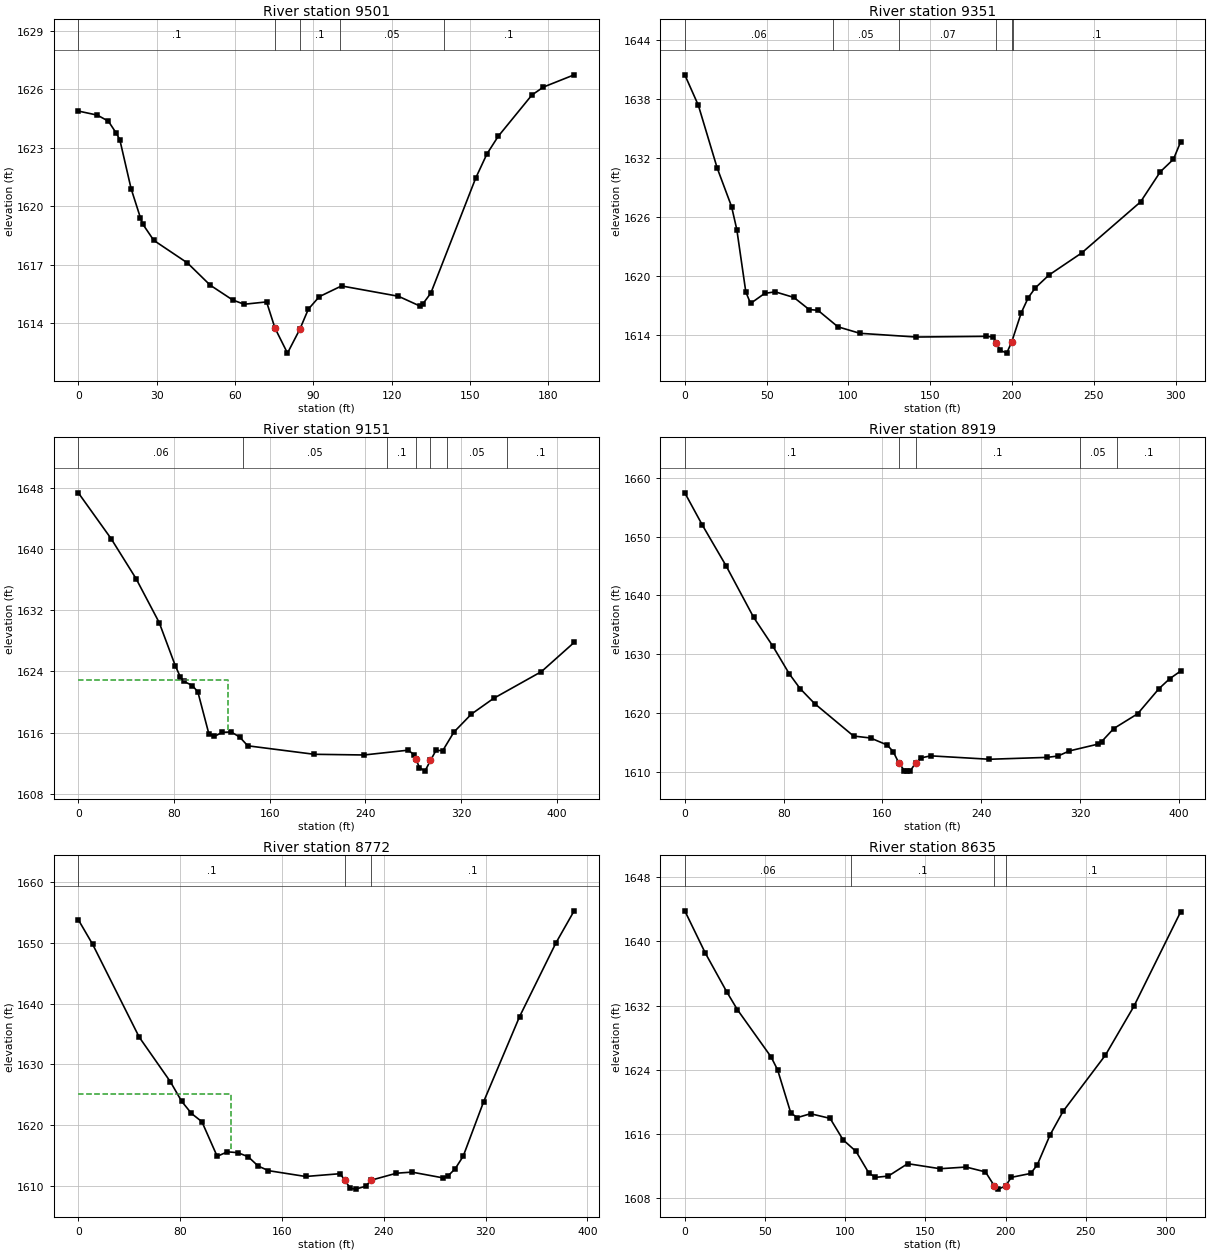
Type RM Length L Ch R = 1 ,9501    ,145.1,149.9,151.8
XS GIS Cut Line= 5
2164598.91187234669985.4243735862164532.16428873669958.144926372
2164514.17146184669956.9840988312164457.57276918669935.566015845
2164421.20414395669920.821978591
#Sta/Elev= 30
       0 1624.89     7.3 1624.68    11.5 1624.37    14.6 1623.74    15.9 1623.41
    20.2 1620.91    23.8  1619.4    24.6  1619.1    28.9 1618.25    41.8 1617.09
    50.5 1615.95    59.1 1615.19    63.5 1614.97    72.1 1615.09    75.3 1613.75
    80.1 1612.46   84.85 1613.69    88.1 1614.72    92.3 1615.36   100.8 1615.91
   122.6 1615.38   130.8 1614.88   131.9 1614.98     135 1615.54   152.2 1621.45
   156.5 1622.69   160.8 1623.59   173.7 1625.71   178.1 1626.12   189.9 1626.75
#Mann= 5 ,-1,0
       0      .1       0    75.3    .045       0   84.85      .1       0
  100.14     .05       0  140.14      .1       0
Bank Sta=75.3,84.85
XS Rating Curve= 0 ,0
Exp/Cntr(USF)=0,0
Exp/Cntr=0.3,0.1

Type RM Length L Ch R = 1 ,9351    ,196,200.3,200.2
XS GIS Cut Line= 4
2164679.23462524669897.4182767922164627.48305448669865.571156324
2164480.19012232669809.0425174952164395.79525308669803.469271414
#Sta/Elev= 30
       0 1640.45     8.3 1637.34    19.8 1630.96    28.6 1627.03    31.8 1624.69
    37.3 1618.34    40.2 1617.17    48.9  1618.2    55.3 1618.35    66.7 1617.78
      76 1616.55    81.4 1616.47    93.6 1614.79     107 1614.13   141.4 1613.75
   184.4 1613.82   188.6 1613.75   190.41613.192   192.8  1612.4   196.8 1612.11
   199.9 1613.28   205.7 1616.23     210 1617.77   214.3 1618.76   222.6 1620.06
   242.6 1622.31   278.6 1627.51   290.7 1630.58   298.7 1631.85   303.1 1633.62
#Mann= 6 ,-1,0
       0     .06       0   90.77     .05       0  130.77     .07       0
   190.4    .045       0   199.9     .07       0  200.77      .1       0
Bank Sta=190.4,199.9
XS Rating Curve= 0 ,0
Exp/Cntr(USF)=0,0
Exp/Cntr=0.3,0.1

Type RM Length L Ch R = 1 ,9151    ,238.3,231.5,219
XS GIS Cut Line= 4
2164781.51436116669833.7806868172164742.59010281669755.047527884
2164534.69917754669633.8515416622164448.88888072669629.428330486
#Sta/Elev= 30
       0 1647.34    27.4 1641.35    48.2 1636.14    67.6 1630.38      81 1624.76
    85.1 1623.33      88 1622.71    95.3 1622.16    99.9 1621.32   109.1 1615.84
   113.8 1615.51   120.2 1616.04   127.7 1616.09   134.8 1615.43   141.6 1614.28
   197.1 1613.17   238.8 1613.08   275.8 1613.71   280.5 1613.11   282.2  1612.5
   285.1 1611.44   289.7 1610.97   294.3 1612.36     299  1613.7   304.5 1613.63
   313.9 1616.07   328.5 1618.42     347 1620.47   387.1 1623.98   414.4 1627.79
#Mann= 7 ,-1,0
       0     .06       0  137.83     .05       0  257.83      .1       0
   282.2    .045       0   294.3      .1       0  307.83     .05       0
  358.47      .1       0
#XS Ineff= 2 , 0
          124.73  1622.9
Permanent Ineff=
       F       F
Bank Sta=282.2,294.3
XS Rating Curve= 0 ,0
Exp/Cntr(USF)=0,0
Exp/Cntr=0.3,0.1

Type RM Length L Ch R = 1 ,8919    ,140,146.9,151.4
XS GIS Cut Line= 4
 2164800.0918481669388.0739014042164716.54230366669442.135371333
2164492.43293741669566.9682200772164455.08137637669592.524551317
#Sta/Elev= 30
       0 1657.45    14.2 1651.96    33.3 1645.07    55.7 1636.26    71.4  1631.3
    84.6 1626.63    93.3 1624.13     105 1621.59   136.6 1616.05   150.3 1615.72
   163.8 1614.53   168.6 1613.42   173.2 1611.49   177.8 1610.15   179.7 1610.08
   182.4  1610.1   186.9 1611.49   191.5 1612.35   199.1 1612.68   246.5  1612.1
   293.2 1612.42     302 1612.65   311.3 1613.52   334.3 1614.67   337.3 1615.09
   347.2 1617.33   366.5 1619.84   383.7  1624.1   392.4  1625.8   401.3 1627.11
#Mann= 5 ,-1,0
       0      .1       0   173.2    .045       0   186.9      .1       0
  319.51     .05       0  349.51      .1       0
Bank Sta=173.2,186.9
XS Rating Curve= 0 ,0
Exp/Cntr(USF)=0,0
Exp/Cntr=0.3,0.1

Type RM Length L Ch R = 1 ,8772    ,137.3,137.2,135.4
XS GIS Cut Line= 4
2164754.07737978669336.9146119542164675.44251443669380.163787897
2164459.19663472 669404.737183322164377.61296191669414.566541489
#Sta/Elev= 30
       0 1653.78    11.3 1649.72    47.8 1634.48    72.3 1627.14    81.1 1623.94
    88.9 1621.91    97.1 1620.55   109.1 1614.86   117.2  1615.6   125.2 1615.46
   133.4  1614.8   141.3 1613.26   149.4  1612.5   178.6 1611.54   205.8    1612
   209.3 1610.92   213.8 1609.59   217.8 1609.46   225.9 1609.94   229.9 1610.92
     250 1612.08   262.1 1612.26   286.3 1611.32   290.3 1611.59   296.1 1612.81
   302.4 1614.87   318.5 1623.86   346.7 1637.84   375.2 1649.94   389.6 1655.25
#Mann= 3 ,-1,0
       0      .1       0   209.3    .045       0   229.9      .1       0
#XS Ineff= 2 , 0
          119.63 1625.03
Permanent Ineff=
       F       F
Bank Sta=209.3,229.9
XS Rating Curve= 0 ,0
Exp/Cntr(USF)=0,0
Exp/Cntr=0.3,0.1

Type RM Length L Ch R = 1 ,8635    ,124.3,126,122.6
XS GIS Cut Line= 4
2164696.57202538669246.2136277712164615.23864372669265.019033936
2164468.55647564669284.7647104092164390.98417521669289.936197104
#Sta/Elev= 30
       0 1643.83    12.8 1638.55    26.1 1633.73    32.8 1631.48    53.8 1625.58
    57.9 1623.95    66.1 1618.57    70.2    1618    78.4 1618.48    90.6  1617.9
    98.7 1615.22   106.8 1613.77   114.8 1611.06   118.9 1610.53   126.9 1610.69
     139 1612.24   159.2 1611.61   175.4 1611.82   187.5 1611.21   193.1 1609.44
   195.5 1609.06     200 1609.45   203.6 1610.53   215.7 1611.02   219.8 1612.09
   227.8 1615.84   235.9 1618.78   262.3  1625.8     280 1631.88   309.2  1643.7
#Mann= 4 ,-1,0
       0     .06       0  103.48      .1       0   193.1    .045       0
     200      .1       0
Bank Sta=193.1,200
XS Rating Curve= 0 ,0
Exp/Cntr(USF)=0,0
Exp/Cntr=0.3,0.1

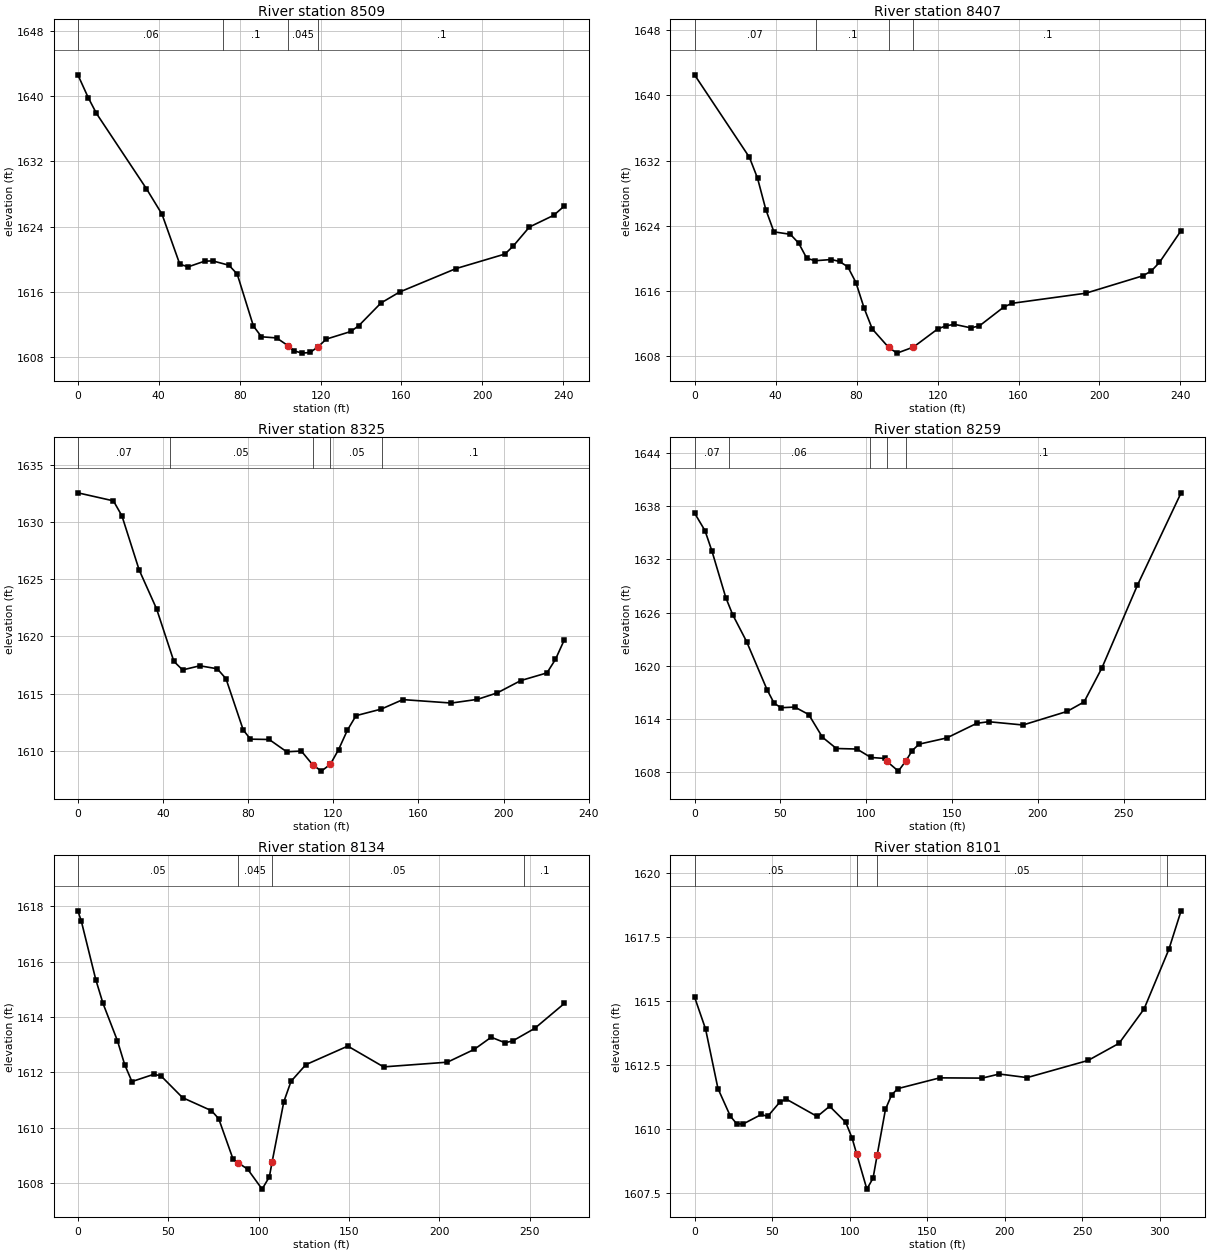
Type RM Length L Ch R = 1 ,8509    ,102,101.6,101
XS GIS Cut Line= 4
2164673.11750492669171.8800361822164613.04467967669186.506463199
2164519.54002124669194.864421494 2164434.9156935669201.655262609
#Sta/Elev= 30
       0  1642.6     5.1 1639.82     9.2 1637.87    33.9 1628.66    41.6 1625.54
    50.4 1619.42    54.5 1619.09    62.7 1619.79    66.7 1619.82    74.7 1619.29
    78.8 1618.21    86.8 1611.85    90.8 1610.53    98.3 1610.39   103.9 1609.44
   106.9 1608.81   110.9 1608.53   114.9 1608.61   118.9 1609.34   122.9 1610.25
     135 1611.18     139 1611.91   149.9 1614.67   159.1 1616.01     187 1618.88
   211.2 1620.66   215.3 1621.64   223.3 1623.97   235.3  1625.4   240.6 1626.55
#Mann= 4 ,-1,0
       0     .06       0   71.83      .1       0   103.9    .045       0
   118.9      .1       0
Bank Sta=103.9,118.9
XS Rating Curve= 0 ,0
Exp/Cntr(USF)=0,0
Exp/Cntr=0.3,0.1

Type RM Length L Ch R = 1 ,8407    ,83.5,82.6,82.9
XS GIS Cut Line= 2
 2164658.8836521669078.7074412112164421.62260462669116.923985772
#Sta/Elev= 30
       0 1642.51    27.1  1632.4    31.1 1629.85    35.2    1626    39.2 1623.27
    47.3 1622.97    51.4  1621.9    55.4 1620.04    59.5 1619.73    67.6 1619.88
    71.6 1619.64    75.7 1618.98    79.7 1617.06    83.8 1613.89    87.8 1611.36
    95.9  1609.1     100 1608.41   108.1 1609.15   120.2 1611.39   124.3 1611.76
   128.3 1611.94   136.4 1611.51   140.6 1611.73   152.7 1614.05   156.7 1614.51
   193.2 1615.75   221.5 1617.89   225.6 1618.48   229.6 1619.52   240.3 1623.42
#Mann= 4 ,-1,0
       0     .07       0      60      .1       0    95.9    .045       0
   108.1      .1       0
Bank Sta=95.9,108.1
XS Rating Curve= 0 ,0
Exp/Cntr(USF)=0,0
Exp/Cntr=0.3,0.1

Type RM Length L Ch R = 1 ,8325    ,63.7,65.8,65.9
XS GIS Cut Line= 3
2164636.59066777668999.089640043 2164603.9473693669004.662886125
2164412.06846848669042.083252674
#Sta/Elev= 30
       0 1632.53    16.7 1631.83    20.7 1630.52    28.8  1625.8      37  1622.4
    45.1 1617.83    49.2 1617.08    57.3 1617.44    65.5 1617.18    69.6 1616.31
    77.7 1611.84    81.1 1611.04    89.9 1611.01    98.1 1609.94     105    1610
   110.3 1608.81   114.4 1608.25   118.6 1608.84   122.5 1610.13   126.6 1611.81
   130.7 1613.09   142.5 1613.66   152.7 1614.49   175.5 1614.19   187.7 1614.51
   197.1 1615.08   208.1 1616.15   220.4 1616.82   224.4    1618   228.6 1619.72
#Mann= 5 ,-1,0
       0     .07       0   43.12     .05       0   110.3    .045       0
   118.6     .05       0  143.12      .1       0
Bank Sta=110.3,118.6
XS Rating Curve= 0 ,0
Exp/Cntr(USF)=0,0
Exp/Cntr=0.3,0.1

Type RM Length L Ch R = 1 ,8259    ,113.6,125.3,126.3
XS GIS Cut Line= 5
2164622.28666019668947.0714301562164560.66248208668953.520472051
2164453.17845051668964.2688752082164402.30267556669003.679686786
2164355.00970167669016.577770576
#Sta/Elev= 30
       0 1637.21     6.1 1635.22    10.2 1632.88    18.2 1627.68    22.2 1625.76
    30.3 1622.73    42.3 1617.27    46.4 1615.76    50.4 1615.27    58.4 1615.34
    66.5  1614.5    74.5 1611.94    82.6 1610.67    94.6 1610.61   102.7 1609.66
   110.7 1609.55     112 1609.23   118.7 1608.12  122.97 1609.24   126.8 1610.44
   130.8 1611.16   146.9 1611.86   164.4 1613.51   171.3 1613.69   191.3 1613.32
     217 1614.85   226.9 1615.92   237.3 1619.76     258 1629.09   283.4 1639.49
#Mann= 5 ,-1,0
       0     .07       0      20     .06       0  101.96     .05       0
     112    .045       0  122.97      .1       0
Bank Sta=112,122.97
XS Rating Curve= 0 ,0
Exp/Cntr(USF)=0,0
Exp/Cntr=0.3,0.1

Type RM Length L Ch R = 1 ,8134    ,41.3,32.7,32.2
XS GIS Cut Line= 5
2164586.10190166668855.6663690162164463.49139298668855.661388669
 2164444.7559128668867.1072218172164421.65133335668889.846291057
2164412.62267469668981.478137208
#Sta/Elev= 30
       0 1617.83     1.9 1617.46     9.9 1615.35    13.9 1614.49    21.9 1613.14
    25.9 1612.28    29.9 1611.67    41.9 1611.93    45.9 1611.88    57.9 1611.09
    73.9 1610.62    77.9 1610.33    85.9 1608.86    88.4 1608.75    93.9 1608.51
   101.9 1607.79   105.9 1608.23   107.4 1608.76   113.9 1610.94   117.9 1611.68
   126.1 1612.28   149.3 1612.95   169.1  1612.2   204.4 1612.37   219.2 1612.83
   228.6 1613.27   236.3 1613.07   240.6 1613.14   252.7 1613.59   269.1 1614.49
#Mann= 4 ,-1,0
       0     .05       0    88.4    .045       0   107.4     .05       0
  246.98      .1       0
Bank Sta=88.4,107.4
XS Rating Curve= 0 ,0
Exp/Cntr(USF)=0,0
Exp/Cntr=0.3,0.1

Type RM Length L Ch R = 1 ,8101    ,22.4,21.9,22.7
XS GIS Cut Line= 5
2164595.24955733668823.0175462692164458.55610219668823.890454184
2164433.49218043668838.8322297632164400.29361109668874.216912798
2164390.08711542668972.999225145
#Sta/Elev= 30
       0 1615.17     7.1 1613.92    15.1 1611.59    23.1 1610.51    27.1 1610.22
    31.1  1610.2    43.1 1610.58    47.1  1610.5    55.1 1611.07    59.1 1611.18
    79.1  1610.5    87.1  1610.9    97.5 1610.27   101.6 1609.65   104.6 1609.02
   111.1 1607.66   115.1 1608.09   117.7 1608.98   123.1 1610.78   127.1 1611.35
   131.1 1611.59   158.1 1612.01   185.4    1612   196.5 1612.16   214.4 1612.02
   253.7 1612.69   273.7 1613.36   289.8  1614.7   305.8 1617.03   313.7 1618.54
#Mann= 4 ,-1,0
       0     .05       0   104.6    .045       0   117.7     .05       0
   304.4      .1       0
Bank Sta=104.6,117.7
XS Rating Curve= 0 ,0
Exp/Cntr(USF)=0,0
Exp/Cntr=0.3,0.1

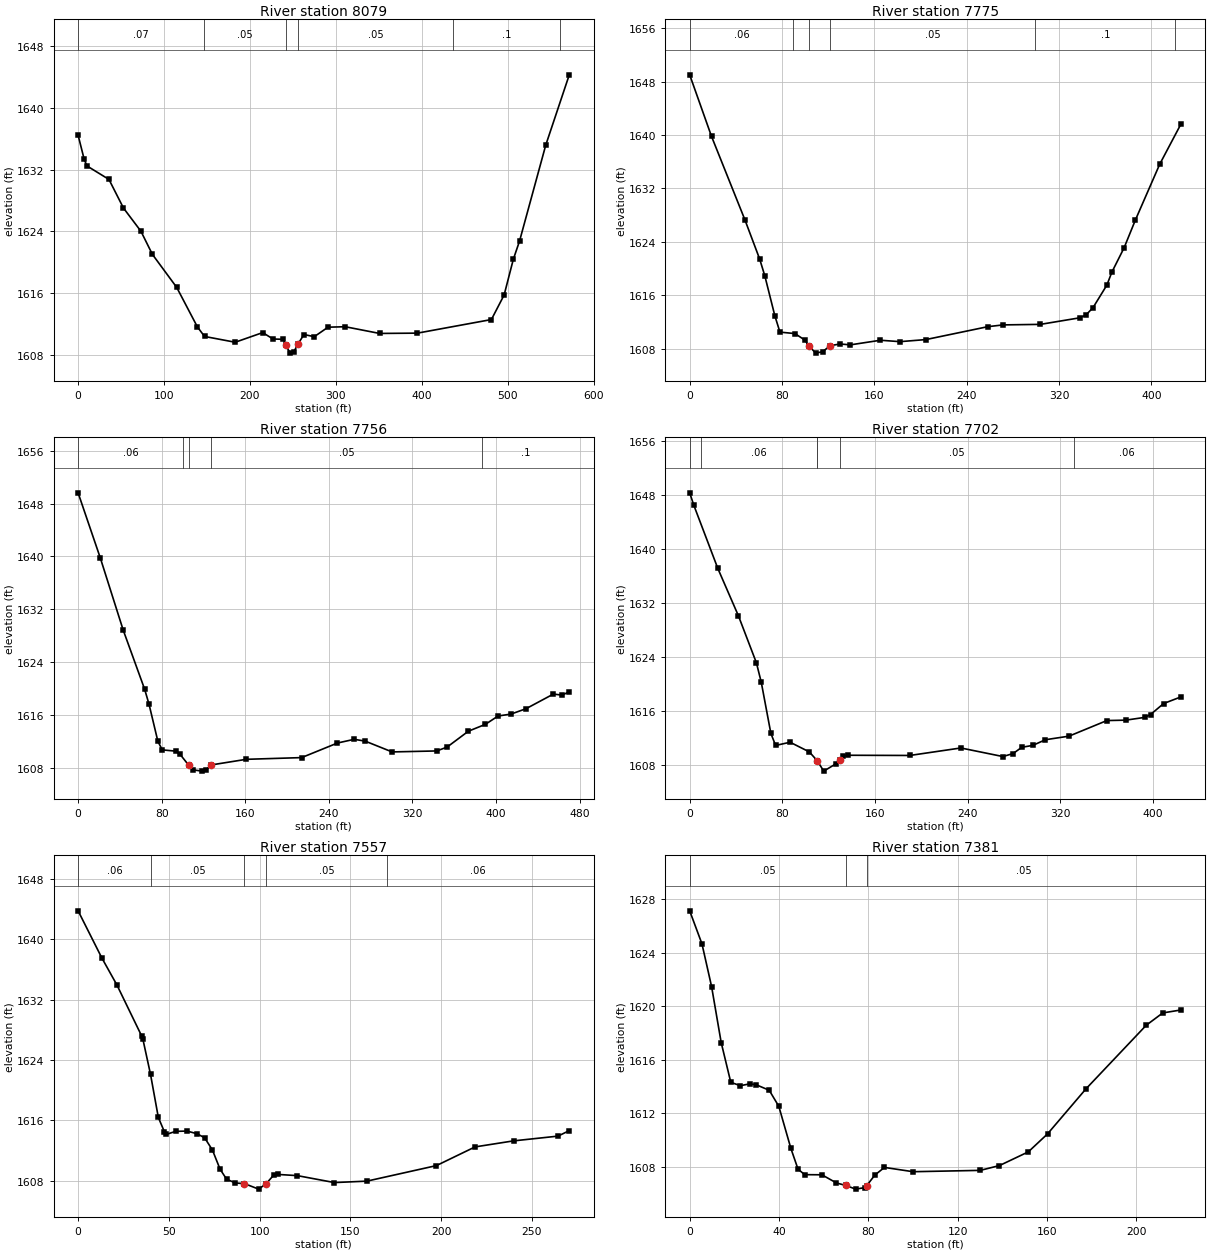
Type RM Length L Ch R = 1 ,8079    ,315.3,304.5,293.2
XS GIS Cut Line= 4
2164738.06679609 668828.394100932164656.48312328 668799.88896224
2164262.11668576668810.2973884422164201.38384006668877.540891774
#Sta/Elev= 30
       0 1636.46     7.1 1633.33    10.3 1632.48    35.9 1630.73    52.8 1627.02
    73.1 1624.02    86.4 1621.03   114.7 1616.75   138.8 1611.63   147.1 1610.39
   182.8 1609.64   214.8 1610.89   226.8 1610.06   238.8 1610.02   241.6 1609.24
   246.8 1608.23   250.8 1608.35   255.6 1609.36   262.8 1610.64   274.8 1610.36
   290.8 1611.59   310.8 1611.65   350.8 1610.78   394.8 1610.82   480.9 1612.58
   495.7 1615.76   506.4 1620.38   513.7 1622.77   544.1 1635.16   571.5 1644.28
#Mann= 6 ,-1,0
       0     .07       0  146.42     .05       0   241.6    .045       0
   255.6     .05       0  436.42      .1       0  560.92     .05       0
Bank Sta=241.6,255.6
XS Rating Curve= 0 ,0
Exp/Cntr(USF)=0,0
Exp/Cntr=0.3,0.1

Type RM Length L Ch R = 1 ,7775    ,19.4,18.4,17.8
XS GIS Cut Line= 4
2164376.52346549668482.8947866162164364.34194191 668530.90432072
2164236.74730892 668825.762055262164199.89409635668866.264395063
#Sta/Elev= 30
       0 1649.03    18.9 1639.81    47.8 1627.32    60.7 1621.39    65.1  1618.9
    73.8 1612.91    78.2 1610.47    91.2 1610.25     100 1609.25   103.1 1608.43
   109.2 1607.32   115.3 1607.54   121.7 1608.44   130.4 1608.69   139.2 1608.56
   165.3 1609.25   182.2 1609.04   204.6 1609.35   258.2 1611.28   271.5 1611.55
   303.9 1611.63   337.9 1612.61   343.4 1613.04   349.5 1614.14   361.5 1617.52
   365.8 1619.45   376.5 1623.14   386.2 1627.27   407.3 1635.64   425.6 1641.63
#Mann= 6 ,-1,0
       0     .06       0   89.53     .05       0   103.1    .045       0
   121.7     .05       0  299.53      .1       0  420.81     .05       0
Bank Sta=103.1,121.7
XS Rating Curve= 0 ,0
Exp/Cntr(USF)=0,0
Exp/Cntr=0.3,0.1

Type RM Length L Ch R = 1 ,7756    ,54.3,54.1,53.4
XS GIS Cut Line= 5
 2164358.6551806668476.9145394672164302.42835224668640.961718964
2164235.12634036668683.8444006822164162.03719889668693.876243629
2164021.23778534668667.853028943
#Sta/Elev= 30
       0 1649.65    21.4 1639.71    43.1 1628.88    63.7 1619.88    67.9 1617.61
    76.4 1611.97    80.6 1610.69    93.3  1610.5    97.5 1610.04   105.8 1608.38
   110.2 1607.66   118.7 1607.47   122.9 1607.68   127.1  1608.4     161 1609.26
     214 1609.52   248.3 1611.73   264.3 1612.29   274.8 1612.02   300.6 1610.38
   343.4 1610.53   353.3 1611.12   373.6 1613.52   389.9 1614.56   402.1 1615.83
   414.3 1616.11   428.8 1616.93     455 1619.15   463.2 1618.99   470.2 1619.49
#Mann= 5 ,-1,0
       0     .06       0     100     .05       0   105.8    .045       0
   127.1     .05       0  386.99      .1       0
Bank Sta=105.8,127.1
XS Rating Curve= 0 ,0
Exp/Cntr(USF)=0,0
Exp/Cntr=0.3,0.1

Type RM Length L Ch R = 1 ,7702    ,143.5,145.4,145.5
XS GIS Cut Line= 5
2164300.74479049668461.7729169692164255.95807436668619.419412274
2164216.13738784668656.1725125042164163.11193226668663.338114609
2164013.51577473668632.886573954
#Sta/Elev= 30
       0 1648.33     3.5 1646.52    24.3 1637.13    42.1 1630.11    57.6 1623.16
    61.8 1620.29    70.1 1612.71    74.2 1610.91    86.7 1611.39   103.3 1609.96
   110.1 1608.66   115.8 1607.11   126.3  1608.2   129.5 1608.79   132.4 1609.35
   136.6 1609.46   190.1 1609.43   234.2 1610.54   270.5 1609.27   279.3 1609.71
   286.8 1610.64   296.3 1610.92   307.2 1611.76   327.6 1612.29   360.3  1614.6
   376.6 1614.66     393 1615.07     398 1615.49   409.3 1617.12   424.2  1618.1
#Mann= 6 ,-1,0
       0      .1       0      10     .06       0     110     .05       0
   110.1    .045       0   129.5     .05       0  331.58     .06       0
Bank Sta=110.1,129.5
XS Rating Curve= 0 ,0
Exp/Cntr(USF)=0,0
Exp/Cntr=0.3,0.1

Type RM Length L Ch R = 1 ,7557    ,175.9,175.9,175.6
XS GIS Cut Line= 3
2164167.45003145668435.6220663072164092.92776956668641.274846724
2164042.05199461668631.243003777
#Sta/Elev= 30
       0 1643.79    13.1 1637.53    21.4 1633.95      35  1627.2    35.7 1626.76
    39.9  1622.1    44.2 1616.39    47.5 1614.51    48.5 1614.13    53.7 1614.54
      60 1614.58    65.5 1614.23    69.7 1613.69      74 1612.07    78.2 1609.53
    81.8  1608.2    86.7 1607.69    91.61607.615    99.5 1606.88   103.7 1607.62
     108 1608.81     110 1608.83   120.8 1608.67   141.2 1607.75   159.1 1607.94
   197.4    1610   218.7 1612.48   239.9 1613.28   264.4 1613.91   270.6 1614.64
#Mann= 5 ,-1,0
       0     .06       0      40     .05       0    91.6    .045       0
   103.7     .05       0     170     .06       0
Bank Sta=91.6,103.7
XS Rating Curve= 0 ,0
Exp/Cntr(USF)=0,0
Exp/Cntr=0.3,0.1

Type RM Length L Ch R = 1 ,7381    ,141.4,142.1,142.3
XS GIS Cut Line= 2
2163997.83142729668416.0669559892163917.41744811668620.684704991
#Sta/Elev= 30
       0 1627.12     5.5 1624.65     9.8 1621.47    14.1 1617.29    18.4 1614.32
    22.7 1614.07      27 1614.21    29.9 1614.13    35.6 1613.73    39.9 1612.53
    45.3 1609.39    48.5 1607.84    51.5 1607.43    59.2 1607.42    65.7 1606.81
    69.8 1606.63    74.3 1606.35    78.6 1606.47    79.21606.597    82.9  1607.4
    87.2 1607.97     100 1607.65   130.1 1607.75   138.7 1608.11   151.6 1609.13
   160.2 1610.47   177.4 1613.83   204.4 1618.58   211.8  1619.5   219.9 1619.72
#Mann= 3 ,-1,0
       0     .05       0    69.8    .045       0    79.2     .05       0
Bank Sta=69.8,79.2
XS Rating Curve= 0 ,0
Exp/Cntr(USF)=0,0
Exp/Cntr=0.3,0.1