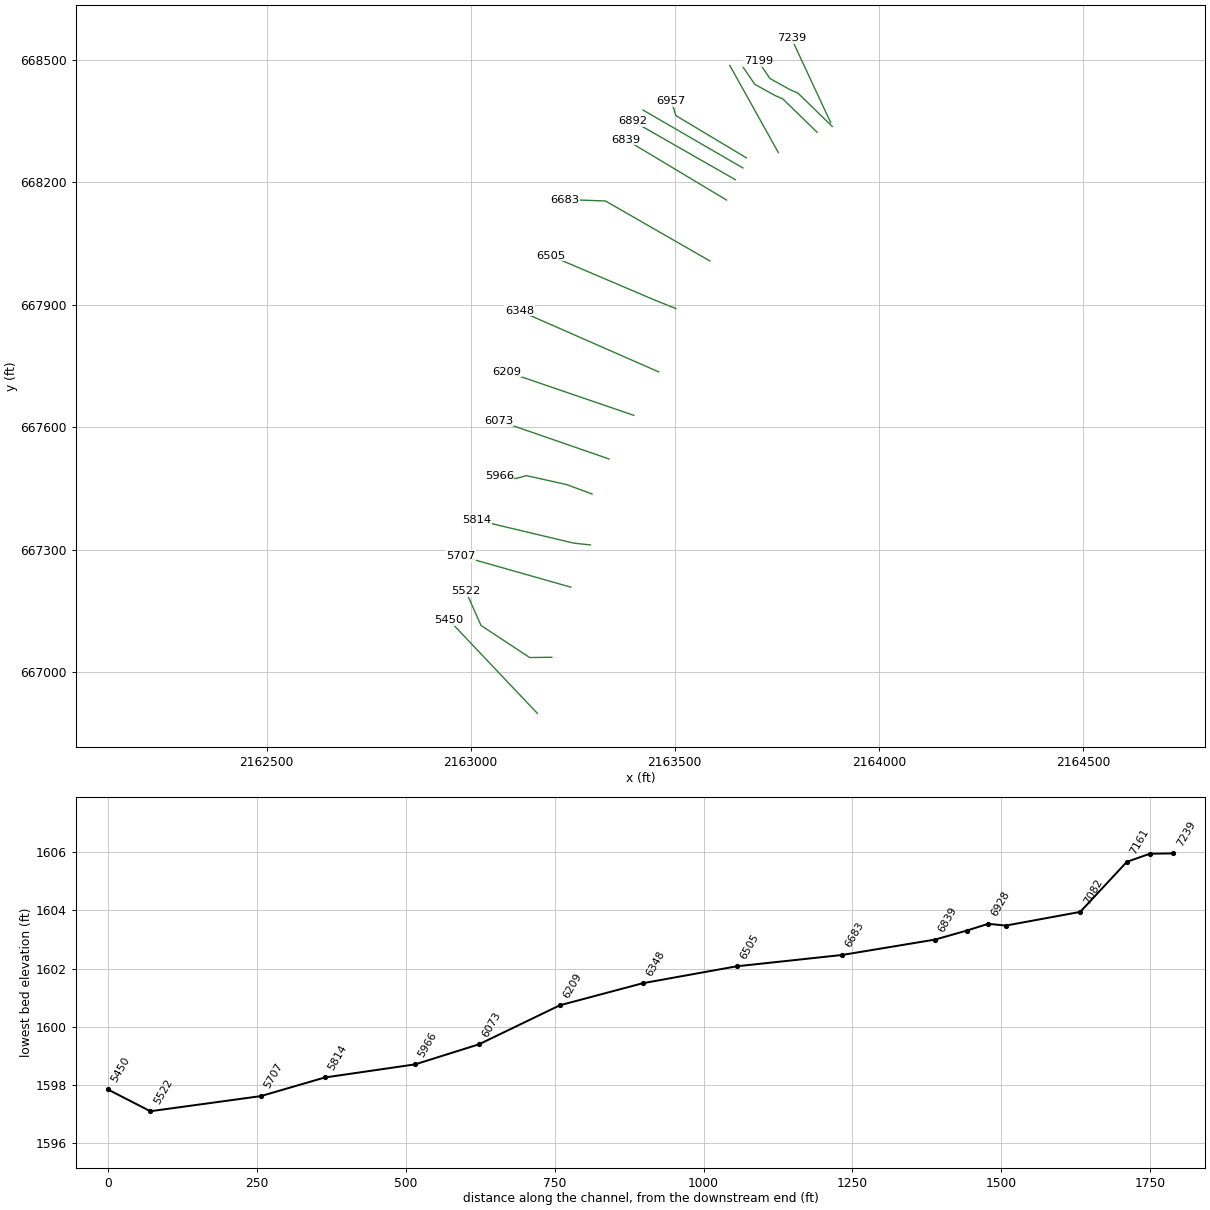
HEC-RAS study KANAWHARN.prj: KANAWHARN

--- KANAWHARN.g01 (geometry) --- (continued)

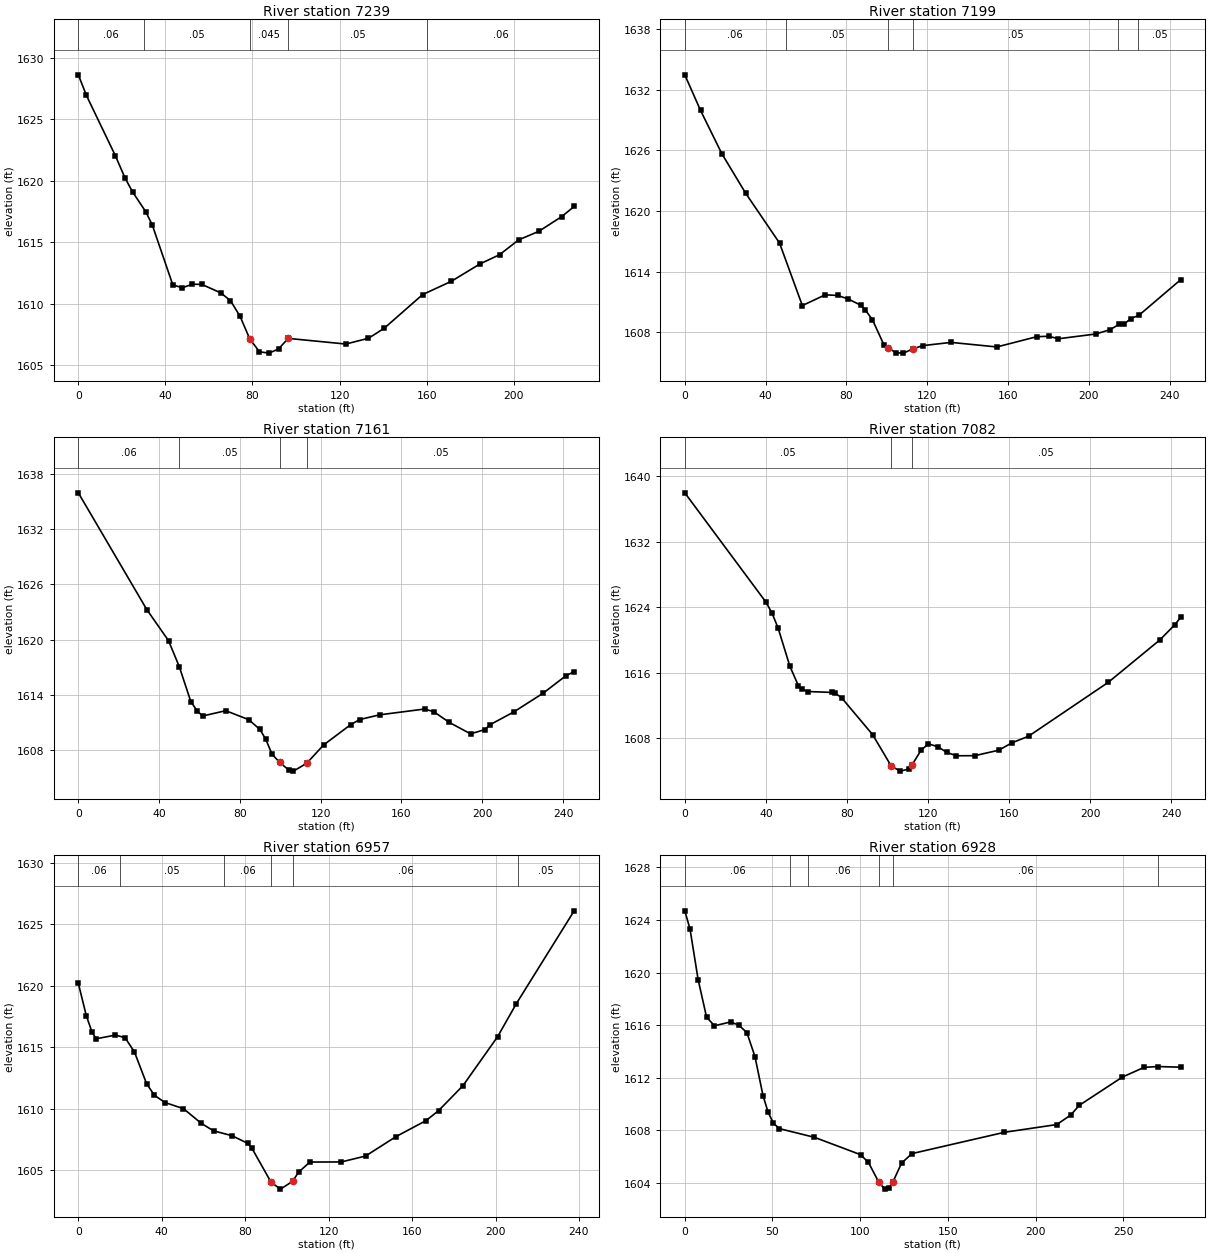
Type RM Length L Ch R = 1 ,7239    ,35.2,39.5,44.2
XS GIS Cut Line= 2
2163881.95243748 668345.807813422163785.75499235668552.280378581
#Sta/Elev= 30
       0 1628.62     3.7 1626.95      17 1622.04    21.4 1620.24    24.9 1619.09
      31 1617.47      34 1616.38    43.4 1611.52    47.8 1611.28    52.3 1611.57
    56.7 1611.56    65.5 1610.86    69.9 1610.23    74.3 1608.96    78.7 1607.14
    83.2 1606.07    87.6 1605.96      92  1606.3    96.4 1607.16   122.9  1606.7
   133.3 1607.17   140.5 1607.98   158.2 1610.73   171.4 1611.81   184.6 1613.23
   193.5 1613.97   202.3 1615.18   211.6 1615.88   222.1 1617.08   227.8  1617.9
#Mann= 5 ,-1,0
       0     .06       0      30     .05       0    78.7    .045       0
    96.4     .05       0     160     .06       0
Bank Sta=78.7,96.4
XS Rating Curve= 0 ,0
Exp/Cntr(USF)=0,0
Exp/Cntr=0.3,0.1

Type RM Length L Ch R = 1 ,7199    ,39.5,38.7,37.6
XS GIS Cut Line= 5
 2163885.7651411668336.422696822 2163801.8856615668417.955897269
 2163783.1154283668426.1678742932163733.25699637  668453.7366543
2163704.51507679668495.969678992
#Sta/Elev= 30
       0 1633.45     7.8 1629.93    18.3 1625.67    30.1 1621.76    46.9 1616.83
    58.2 1610.65    69.5 1611.71    75.7 1611.65    80.9  1611.3    87.2 1610.68
    89.3 1610.24    92.9 1609.25    98.6 1606.77   100.7  1606.5   104.4 1605.99
   108.2 1605.95     1131606.369   117.7 1606.69   131.9 1607.01   154.5 1606.56
   174.2 1607.57   180.1 1607.62     185 1607.37   203.5 1607.84   210.6 1608.27
     215 1608.79   217.7 1608.83   220.7 1609.36   224.8 1609.68   245.5  1613.2
#Mann= 6 ,-1,0
       0     .06       0      50     .05       0   100.7    .045       0
     113     .05       0  214.44     .06       0  224.44     .05       0
Bank Sta=100.7,113
XS Rating Curve= 0 ,0
Exp/Cntr(USF)=0,0
Exp/Cntr=0.3,0.1

Type RM Length L Ch R = 1 ,7161    ,81,78.3,74.7
XS GIS Cut Line= 5
 2163848.5179596668322.345021925   2163764.63848668403.878222372
 2163745.8682468668412.0901993952163696.00981487668439.658979402
2163667.26789529668481.892004094
#Sta/Elev= 30
       0 1635.97    33.9 1623.26    44.7 1619.86      50 1617.03    55.7 1613.24
    58.8 1612.24    61.5 1611.67      73 1612.25    84.4 1611.27    89.9 1610.21
    92.8 1609.14    95.9 1607.52    99.71606.613   104.1 1605.81   106.5 1605.67
   113.1 1606.53   121.4 1608.51   134.9 1610.74   139.4 1611.29   149.2  1611.8
   171.4 1612.43     176 1612.14   183.7 1610.97   194.2 1609.73   201.3 1610.19
     204 1610.74   215.5  1612.1   230.1 1614.15   241.5 1616.07   245.5  1616.5
#Mann= 4 ,-1,0
       0     .06       0      50     .05       0    99.7    .045       0
   113.1     .05       0
Bank Sta=99.7,113.1
XS Rating Curve= 0 ,0
Exp/Cntr(USF)=0,0
Exp/Cntr=0.3,0.1

Type RM Length L Ch R = 1 ,7082    ,118.8,124.8,129.6
XS GIS Cut Line= 2
2163753.77885824668272.2765647462163634.79403529668485.868832296
#Sta/Elev= 30
       0    1638    40.1  1624.6      43 1623.28      46 1621.47    51.8 1616.79
      56 1614.41    57.7 1613.99    60.6 1613.69    72.4 1613.58    74.3 1613.47
    77.3 1612.93    92.6 1608.42   101.8 1604.57   101.8 1604.56   106.3 1603.95
   110.6 1604.22   111.9 1604.65   116.5  1606.5   120.1 1607.29   124.7 1606.94
   129.2 1606.25   133.8 1605.83     143 1605.84   154.8 1606.51   161.3 1607.41
   169.5 1608.22   208.8 1614.81   234.2 1619.99   241.7 1621.87   244.5 1622.77
#Mann= 3 ,-1,0
       0     .05       0   101.8    .045       0   111.9     .05       0
Bank Sta=101.8,111.9
XS Rating Curve= 0 ,0
Exp/Cntr(USF)=0,0
Exp/Cntr=0.3,0.1

Type RM Length L Ch R = 1 ,6957    ,30.3,29.7,29.3
XS GIS Cut Line= 3
2163675.42299922668259.5074617952163503.04010938668362.821112947
2163491.43183397668397.645939178
#Sta/Elev= 30
       0 1620.21     3.8 1617.59     6.5 1616.27     8.5  1615.7    17.8    1616
    22.4 1615.79    26.9 1614.63    32.7 1612.06    36.4 1611.12    41.5 1610.52
    50.4 1610.02      59 1608.82    64.8 1608.22    73.7 1607.82    81.1 1607.21
    83.1 1606.84    92.4 1604.04    96.9 1603.48   102.7 1604.11   105.6 1604.86
     111 1605.68   126.1 1605.69   137.7 1606.17   152.3 1607.75   166.7 1609.05
   172.7 1609.86   184.4 1611.89     201 1615.87     210 1618.56   237.7  1626.1
#Mann= 6 ,-1,0
       0     .06       0      20     .05       0      70     .06       0
    92.4    .045       0   102.7     .06       0  210.97     .05       0
Bank Sta=92.4,102.7
XS Rating Curve= 0 ,0
Exp/Cntr(USF)=0,0
Exp/Cntr=0.3,0.1

Type RM Length L Ch R = 1 ,6928    ,35.9,35.6,36
XS GIS Cut Line= 2
2163666.78805808668234.8127210382163422.22375092    668376.55847
#Sta/Elev= 30
       0  1624.7       3  1623.3     7.6 1619.47    12.4 1616.62    16.9 1615.96
    26.1 1616.25    30.8 1616.01    35.4 1615.44      40 1613.62    44.6 1610.65
    47.5 1609.39    50.5 1608.56    53.9 1608.14    73.9 1607.48   100.2 1606.16
   104.7 1605.57   110.6 1604.07     114 1603.54   116.4 1603.66   118.6 1604.07
   123.6 1605.52   129.5 1606.24   182.2 1607.86   212.1 1608.45   220.1 1609.18
   224.9 1609.91   249.5 1612.06   261.9  1612.8     270 1612.86   282.7 1612.81
#Mann= 6 ,-1,0
       0     .06       0      60     .05       0      70     .06       0
   110.6    .045       0   118.6     .06       0     270     .05       0
Bank Sta=110.6,118.6
XS Rating Curve= 0 ,0
Exp/Cntr(USF)=0,0
Exp/Cntr=0.3,0.1

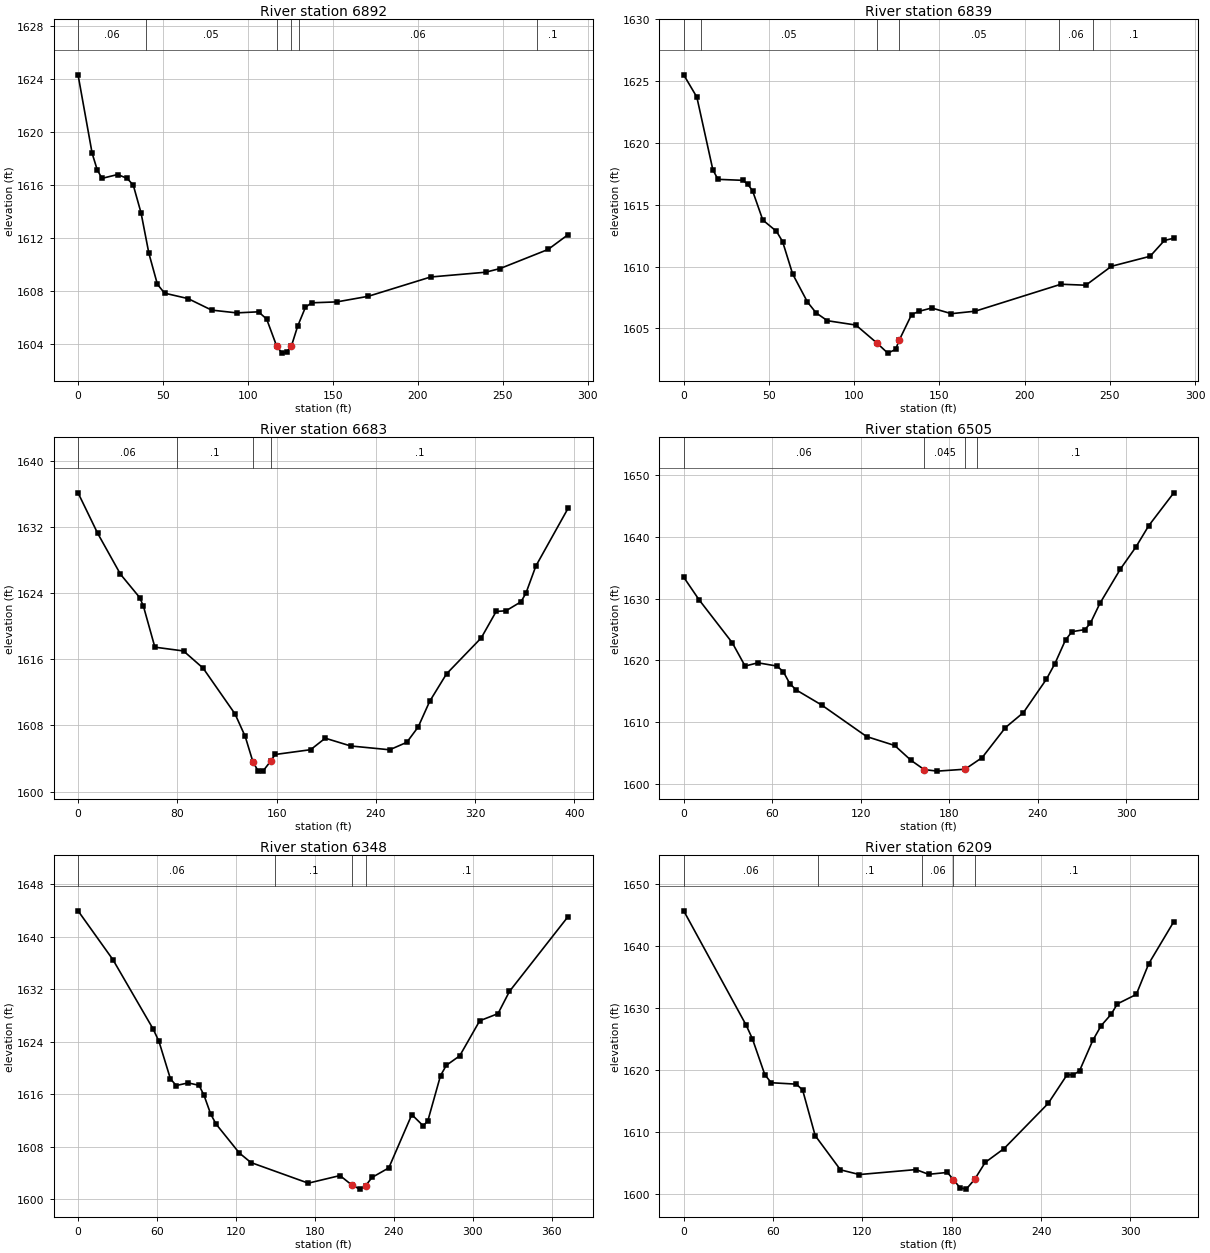
Type RM Length L Ch R = 1 ,6892    ,53.9,53.2,52.5
XS GIS Cut Line= 2
2163648.39484256668206.0179895142163397.90683245668349.033103393
#Sta/Elev= 30
       0 1624.33     8.3  1618.4    11.3 1617.15    14.1 1616.51    23.3  1616.8
    28.9 1616.51    32.5    1616    37.1 1613.89    41.7 1610.84    46.7 1608.51
    50.9 1607.84    64.7 1607.43    78.6 1606.56    93.4 1606.35   106.2 1606.43
     111 1605.88   116.8 1603.87     120 1603.31   122.7 1603.39   125.6 1603.86
   129.2 1605.33   133.8 1606.77   137.4 1607.11   152.3 1607.18   170.7  1607.6
   207.5 1609.06   239.8 1609.42   248.4  1609.7   276.6 1611.14   288.4 1612.26
#Mann= 6 ,-1,0
       0     .06       0      40     .05       0   116.8    .045       0
   125.6     .05       0     130     .06       0     270      .1       0
Bank Sta=116.8,125.6
XS Rating Curve= 0 ,0
Exp/Cntr(USF)=0,0
Exp/Cntr=0.3,0.1

Type RM Length L Ch R = 1 ,6839    ,155.3,156.3,156.2
XS GIS Cut Line= 2
2163626.80112461668156.1782055542163380.24135489668304.009592905
#Sta/Elev= 30
       0  1625.5     7.7  1623.7    17.1 1617.82    20.1 1617.05    34.7 1616.97
    37.6 1616.65    40.4 1616.12    46.4 1613.76    54.4 1612.85      58 1612.02
    63.9  1609.4    72.6 1607.13    77.7 1606.25    84.3 1605.62     101 1605.27
   113.4 1603.81   119.7    1603   124.3  1603.3   126.4 1604.04   133.7 1606.12
   138.3 1606.39   145.5 1606.65     157 1606.19     171 1606.39   221.3 1608.57
   235.9 1608.49   250.9 1610.02   273.6 1610.83     282 1612.11   287.5 1612.29
#Mann= 6 ,-1,0
       0     .06       0      10     .05       0   113.4    .045       0
   126.4     .05       0     220     .06       0     240      .1       0
Bank Sta=113.4,126.4
XS Rating Curve= 0 ,0
Exp/Cntr(USF)=0,0
Exp/Cntr=0.3,0.1

Type RM Length L Ch R = 1 ,6683    ,169.7,177.2,180.3
XS GIS Cut Line= 3
2163585.87367418668006.9783940962163330.21206821 668153.82900514
2163230.24749563668157.367574081
#Sta/Elev= 30
       0  1636.1    15.8 1631.21    34.2 1626.26    49.7 1623.44    52.7 1622.39
    61.9 1617.45      85 1616.99   100.8 1614.91   126.5 1609.38   134.7 1606.66
   140.9  1603.6     145 1602.52     149 1602.47   155.2 1603.67   158.8 1604.48
   187.4 1605.06   199.2 1606.45   219.7 1605.51   251.1 1605.05   264.9 1605.95
   274.1 1607.81   283.3 1610.89   296.9 1614.22   324.9 1618.57   336.9 1621.76
   344.9 1621.85   356.9 1622.93   360.9 1623.97   368.9 1627.25   394.9 1634.24
#Mann= 4 ,-1,0
       0     .06       0      80      .1       0   140.9    .045       0
   155.2      .1       0
Bank Sta=140.9,155.2
XS Rating Curve= 0 ,0
Exp/Cntr(USF)=0,0
Exp/Cntr=0.3,0.1

Type RM Length L Ch R = 1 ,6505    ,158.9,157.2,156.5
XS GIS Cut Line= 3
2163502.71730407667890.2056190492163447.86948549 667912.32167493
2163196.63109069668019.363385389
#Sta/Elev= 30
       0 1633.45    10.4  1629.8    32.9 1622.85    41.6 1619.08    50.3  1619.6
    63.2 1619.08    67.5 1618.17    71.9 1616.24    76.2 1615.22    93.6 1612.76
     124 1607.67     143 1606.23   154.1 1603.82     163 1602.33   171.9 1602.08
   190.7 1602.39   202.3 1604.27   218.1 1609.13   230.3 1611.56   245.8 1616.93
   251.6 1619.46   258.8  1623.3   263.2 1624.64   271.9 1624.97   275.6 1625.98
   282.1 1629.21     296 1634.77   306.5 1638.33   315.3 1641.81   332.2  1647.1
#Mann= 4 ,-1,0
       0     .06       0     163    .045       0   190.7     .06       0
  199.14      .1       0
Bank Sta=163,190.7
XS Rating Curve= 0 ,0
Exp/Cntr(USF)=0,0
Exp/Cntr=0.3,0.1

Type RM Length L Ch R = 1 ,6348    ,138.5,139.5,140.2
XS GIS Cut Line= 2
2163460.46099168667735.1969769772163119.33237484 667884.86210136
#Sta/Elev= 30
       0 1643.97    26.5 1636.52    57.1 1625.93    61.5 1624.04    70.2 1618.34
    74.6 1617.31    83.7 1617.71      92 1617.34    95.8 1615.79   100.8 1612.97
   104.9 1611.43   122.6 1607.01   131.4 1605.56     175 1602.41   199.1 1603.57
   208.2 1602.11   214.2  1601.5   218.7 1602.04   223.4 1603.28   236.2 1604.74
   253.7 1612.87   262.4 1611.15   265.9 1611.95   275.5 1618.81   279.9 1620.39
   290.1 1621.84   305.3 1627.19   319.2 1628.28   327.9 1631.67   372.5  1643.1
#Mann= 4 ,-1,0
       0     .06       0     150      .1       0   208.2    .045       0
   218.7      .1       0
Bank Sta=208.2,218.7
XS Rating Curve= 0 ,0
Exp/Cntr(USF)=0,0
Exp/Cntr=0.3,0.1

Type RM Length L Ch R = 1 ,6209    ,137.1,135.6,135.4
XS GIS Cut Line= 2
2163399.78594125667628.678555119 2163088.3206824667735.196976977
#Sta/Elev= 30
       0  1645.6    41.9 1627.19    46.1    1625    54.5 1619.18    58.8 1617.89
    75.7 1617.66    79.9  1616.7    88.3 1609.37   105.3 1603.85     118 1603.09
     156 1603.89   164.5 1603.13   177.1 1603.43   181.1 1602.29   185.6 1600.96
   189.8 1600.74   195.4  1602.3   202.5 1605.04   215.2 1607.28   244.8 1614.55
   257.5 1619.17   261.7 1619.15   265.9 1619.82   274.8 1624.72   280.4 1627.09
   287.1 1628.92   291.3  1630.6     304 1632.12   312.4 1637.09   329.2 1643.85
#Mann= 5 ,-1,0
       0     .06       0      90      .1       0     160     .06       0
   181.1    .045       0   195.4      .1       0
Bank Sta=181.1,195.4
XS Rating Curve= 0 ,0
Exp/Cntr(USF)=0,0
Exp/Cntr=0.3,0.1

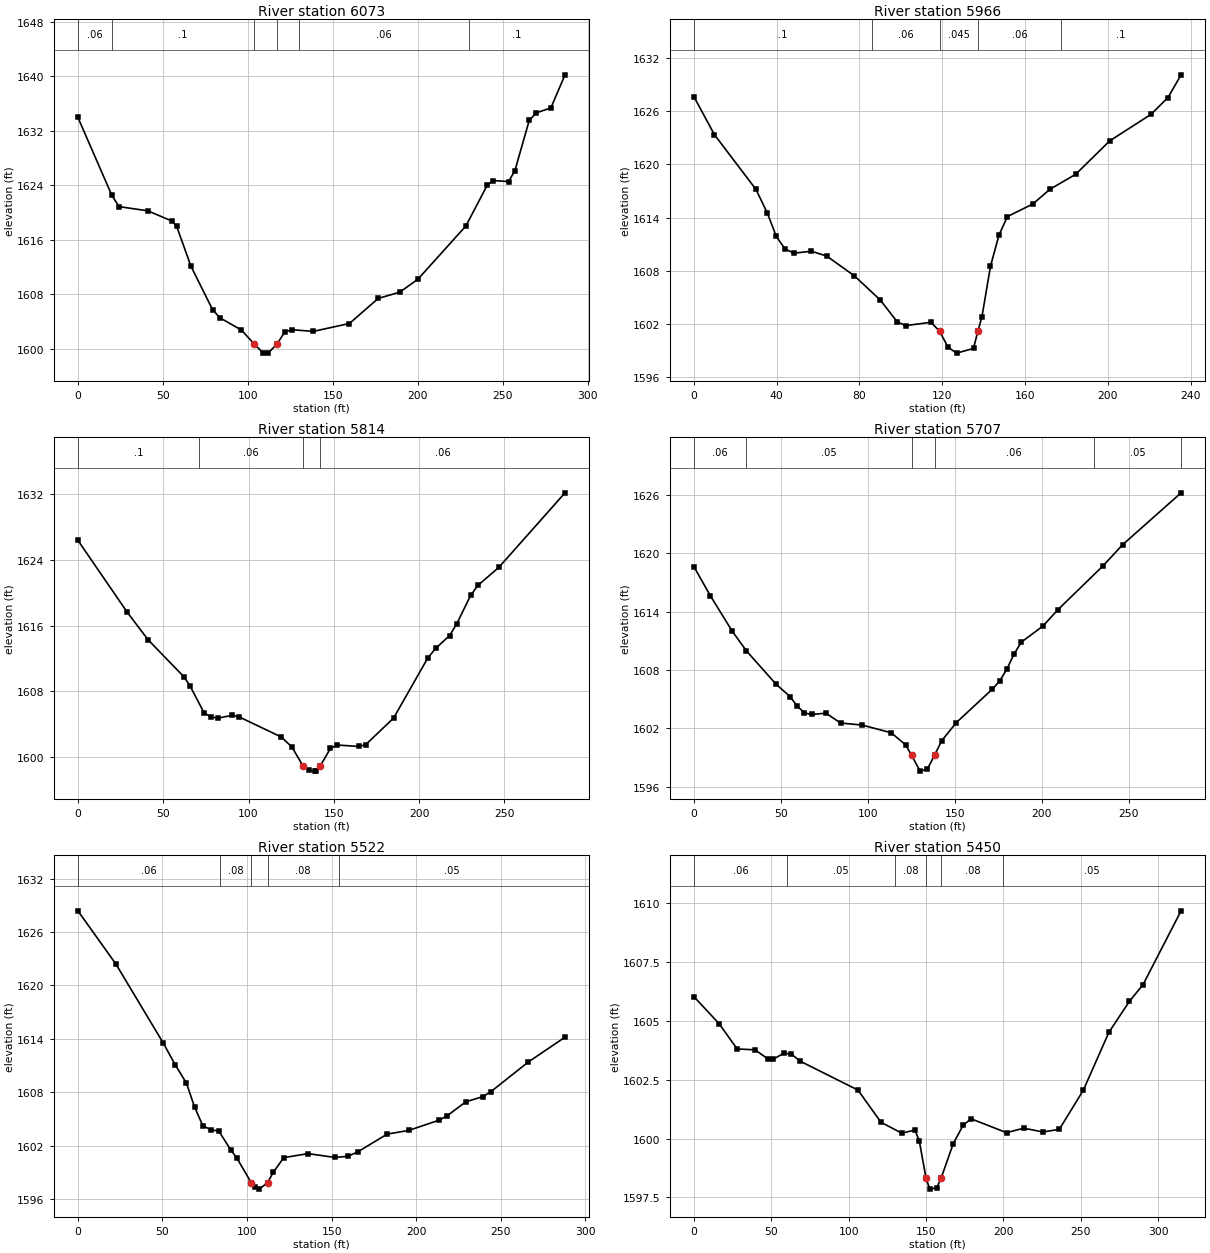
Type RM Length L Ch R = 1 ,6073    ,107.4,107.3,109
XS GIS Cut Line= 2
2163339.04298996667521.7367060462163068.34246599667615.508782978
#Sta/Elev= 30
       0 1633.95      20 1622.51    24.2 1620.87    41.1 1620.26    55.3 1618.76
    58.1 1617.98    66.5 1612.13    79.2 1605.78    83.5 1604.58    96.2 1602.78
  103.61 1600.76   108.9 1599.44   111.9  1599.4   117.3 1600.79   121.6 1602.48
   125.8 1602.83   138.5 1602.59   159.7 1603.74   176.6 1607.41   189.3 1608.34
   199.9 1610.21   228.2 1618.04   240.8 1624.03   244.3 1624.69   253.3 1624.55
     257 1626.13   265.5 1633.55   269.7 1634.62   278.2 1635.35   286.5 1640.19
#Mann= 6 ,-1,0
       0     .06       0      20      .1       0  103.61    .045       0
   117.3      .1       0     130     .06       0     230      .1       0
Bank Sta=103.61,117.3
XS Rating Curve= 0 ,0
Exp/Cntr(USF)=0,0
Exp/Cntr=0.3,0.1

Type RM Length L Ch R = 1 ,5966    ,150.6,151.4,149.8
XS GIS Cut Line= 5
 2163297.4648049667435.9264092312163235.53984844667458.927107347
 2163136.4599181667481.0431632272163110.80529328667473.966025345
 2163069.9516479667479.358008233
#Sta/Elev= 30
       0 1627.62     9.9 1623.34      30 1617.16    35.5 1614.49    39.8 1611.87
      44 1610.46    48.3 1609.98    56.8  1610.2    64.2 1609.65    77.5 1607.43
      90 1604.71    98.2 1602.25   102.3 1601.81   114.6 1602.19   118.7 1601.17
   122.8 1599.38   126.9 1598.71   135.1 1599.24  137.18 1601.16   139.2 1602.84
   143.3  1608.5   147.4 1612.02   151.5 1614.11   163.8 1615.53     172 1617.18
   184.5 1618.88   200.9 1622.64   220.8 1625.62   229.1 1627.53   235.4 1630.09
#Mann= 5 ,-1,0
       0      .1       0   86.06     .06       0   118.7    .045       0
  137.18     .06       0  177.58      .1       0
Bank Sta=118.7,137.18
XS Rating Curve= 0 ,0
Exp/Cntr(USF)=0,0
Exp/Cntr=0.3,0.1

Type RM Length L Ch R = 1 ,5814    ,107.4,107.5,106.8
XS GIS Cut Line= 3
2163293.04159373667311.1918540682163252.34805091667315.615065244
2163014.37928964667372.232168297
#Sta/Elev= 30
       0 1626.39      29  1617.6    41.1 1614.28    62.3 1609.72    65.8 1608.61
      74 1605.35    78.1 1604.85    82.2 1604.72    90.5 1605.07    94.6 1604.86
   119.2 1602.42   125.4 1601.21   132.1 1598.84   135.4 1598.37   138.7 1598.26
   139.8 1598.26     142 1598.86     148 1601.03   152.1 1601.44   164.5 1601.27
   168.6 1601.47     185 1604.72   205.1 1612.06   209.7 1613.22   217.9 1614.79
     222  1616.2   230.2 1619.68   234.4 1620.89   246.7 1623.09   285.5 1632.18
#Mann= 4 ,-1,0
       0      .1       0   70.93     .06       0   132.1    .045       0
     142     .06       0
Bank Sta=132.1,142
XS Rating Curve= 0 ,0
Exp/Cntr(USF)=0,0
Exp/Cntr=0.3,0.1

Type RM Length L Ch R = 1 ,5707    ,187.1,185.4,181.4
XS GIS Cut Line= 2
 2163245.2381485667207.7785116242162975.84092461 667284.22907516
#Sta/Elev= 30
       0 1618.61     9.4 1615.64    21.9 1612.02    30.2 1609.96    47.3 1606.53
    55.2 1605.28    59.3 1604.32    63.5  1603.6    67.6 1603.44    75.9 1603.57
    84.3 1602.56    96.7 1602.35   113.4 1601.56   121.7 1600.31   125.1 1599.25
     130 1597.62   134.2 1597.83   138.3 1599.26   142.5 1600.76   150.8  1602.6
   171.6 1606.05   175.7 1606.87   179.9  1608.1   184.1 1609.68   188.2 1610.87
   200.7 1612.53     209 1614.16   235.2 1618.71   246.4 1620.87     280  1626.2
#Mann= 6 ,-1,0
       0     .06       0      30     .05       0   125.1    .045       0
   138.3     .06       0     230     .05       0     280     .06       0
Bank Sta=125.1,138.3
XS Rating Curve= 0 ,0
Exp/Cntr(USF)=0,0
Exp/Cntr=0.3,0.1

Type RM Length L Ch R = 1 ,5522    ,73,71.5,68.4
XS GIS Cut Line= 4
2163198.69693363667035.9806861722163144.52498171667035.335781982
2163025.21770666667114.0140930972162988.45816786667197.206733537
#Sta/Elev= 30
       0 1628.38    22.5 1622.39    50.5 1613.51    57.5 1611.09    64.2    1609
      69 1606.32    73.8 1604.25    78.6 1603.76    83.3 1603.63    90.4  1601.5
    93.9 1600.62   102.5 1597.82   104.8 1597.35   107.3  1597.1   112.1 1597.83
   115.6 1599.01   121.7 1600.64   136.1 1601.09     152 1600.66   159.7 1600.79
   165.5 1601.29   182.8 1603.28   195.6  1603.7   213.7 1604.86   218.5 1605.37
   229.4 1606.92   239.3 1607.49   244.3 1608.07   266.1 1611.36     288 1614.18
#Mann= 5 ,-1,0
       0     .06       0   84.18     .08       0   102.5    .045       0
   112.1     .08       0  154.18     .05       0
Bank Sta=102.5,112.1
XS Rating Curve= 0 ,0
Exp/Cntr(USF)=0,0
Exp/Cntr=0.3,0.1

Type RM Length L Ch R = 1 ,5450    ,40,40.1,39.8
XS GIS Cut Line= 2
2163163.37236013666898.5305920442162946.81194096 667127.03368139
#Sta/Elev= 30
       0 1606.03    16.3 1604.88    27.9 1603.81    39.5 1603.77    47.7 1603.39
    51.2 1603.37    57.9 1603.62    62.8  1603.6    68.6 1603.29     106 1602.06
   120.9 1600.69   134.3 1600.23   142.8 1600.36   145.6 1599.91     150 1598.31
   152.4 1597.85   156.9 1597.91   159.8 1598.33   167.5 1599.77   173.9 1600.56
   179.1 1600.84     202 1600.25   213.1 1600.44   225.6 1600.28   236.1 1600.39
   251.6 1602.05   268.2 1604.52   281.4 1605.83   290.2 1606.54   314.8 1609.68
#Mann= 6 ,-1,0
       0     .06       0      60     .05       0     130     .08       0
     150    .045       0   159.8     .08       0     200     .05       0
Bank Sta=150,159.8
XS Rating Curve= 0 ,0
Exp/Cntr(USF)=0,0
Exp/Cntr=0.3,0.1