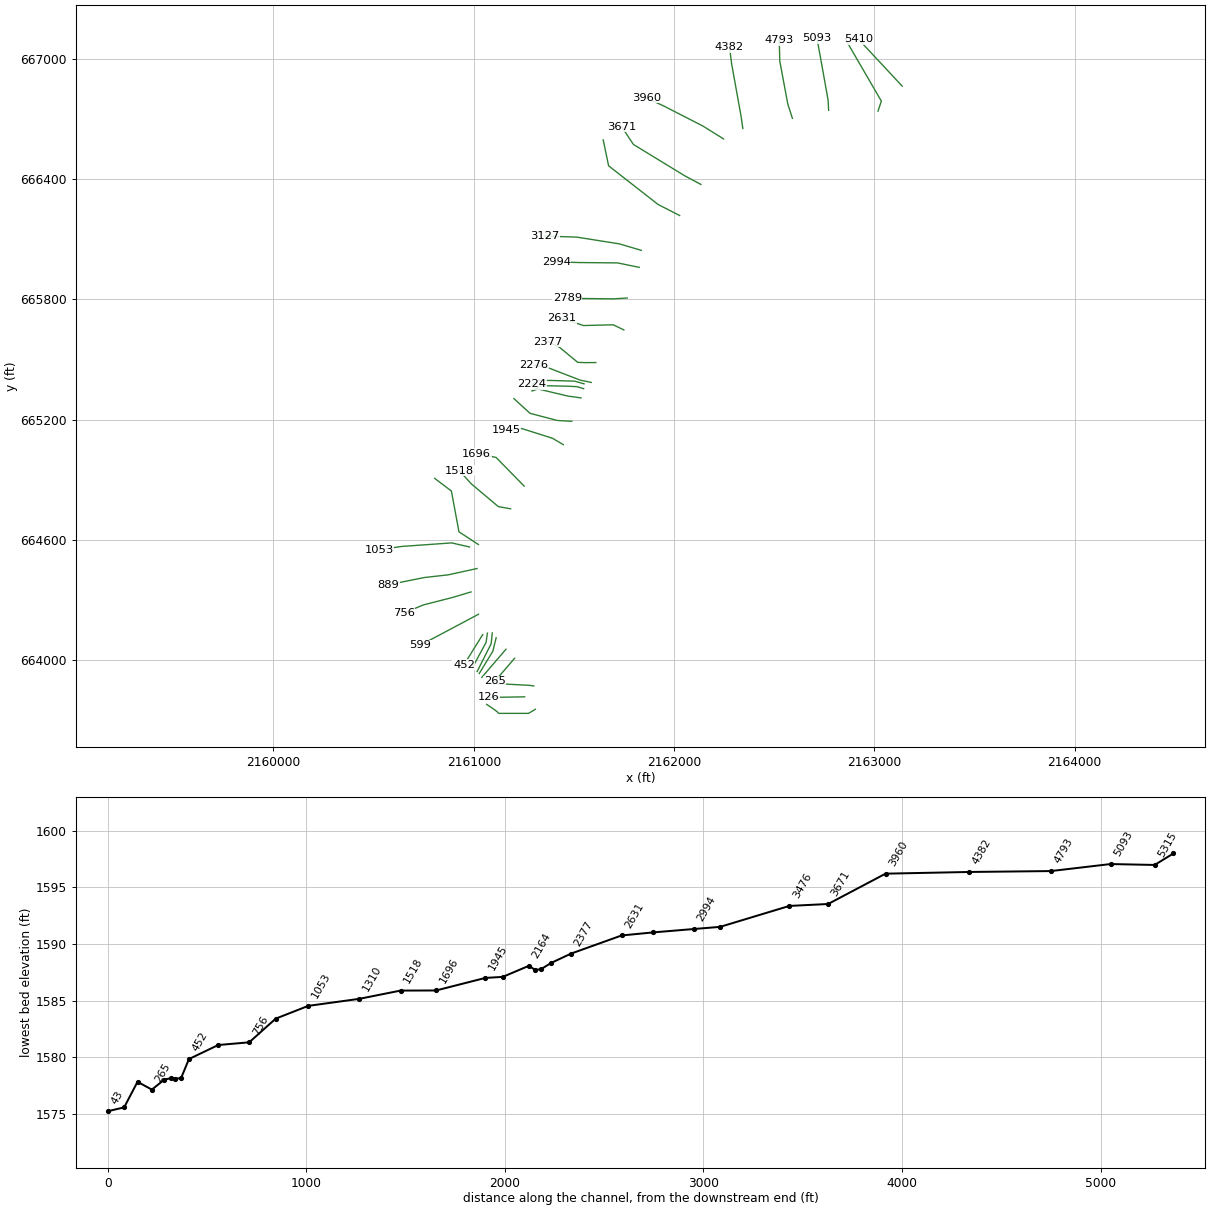
HEC-RAS study KANAWHARN.prj: KANAWHARN

--- KANAWHARN.g01 (geometry) --- (continued)

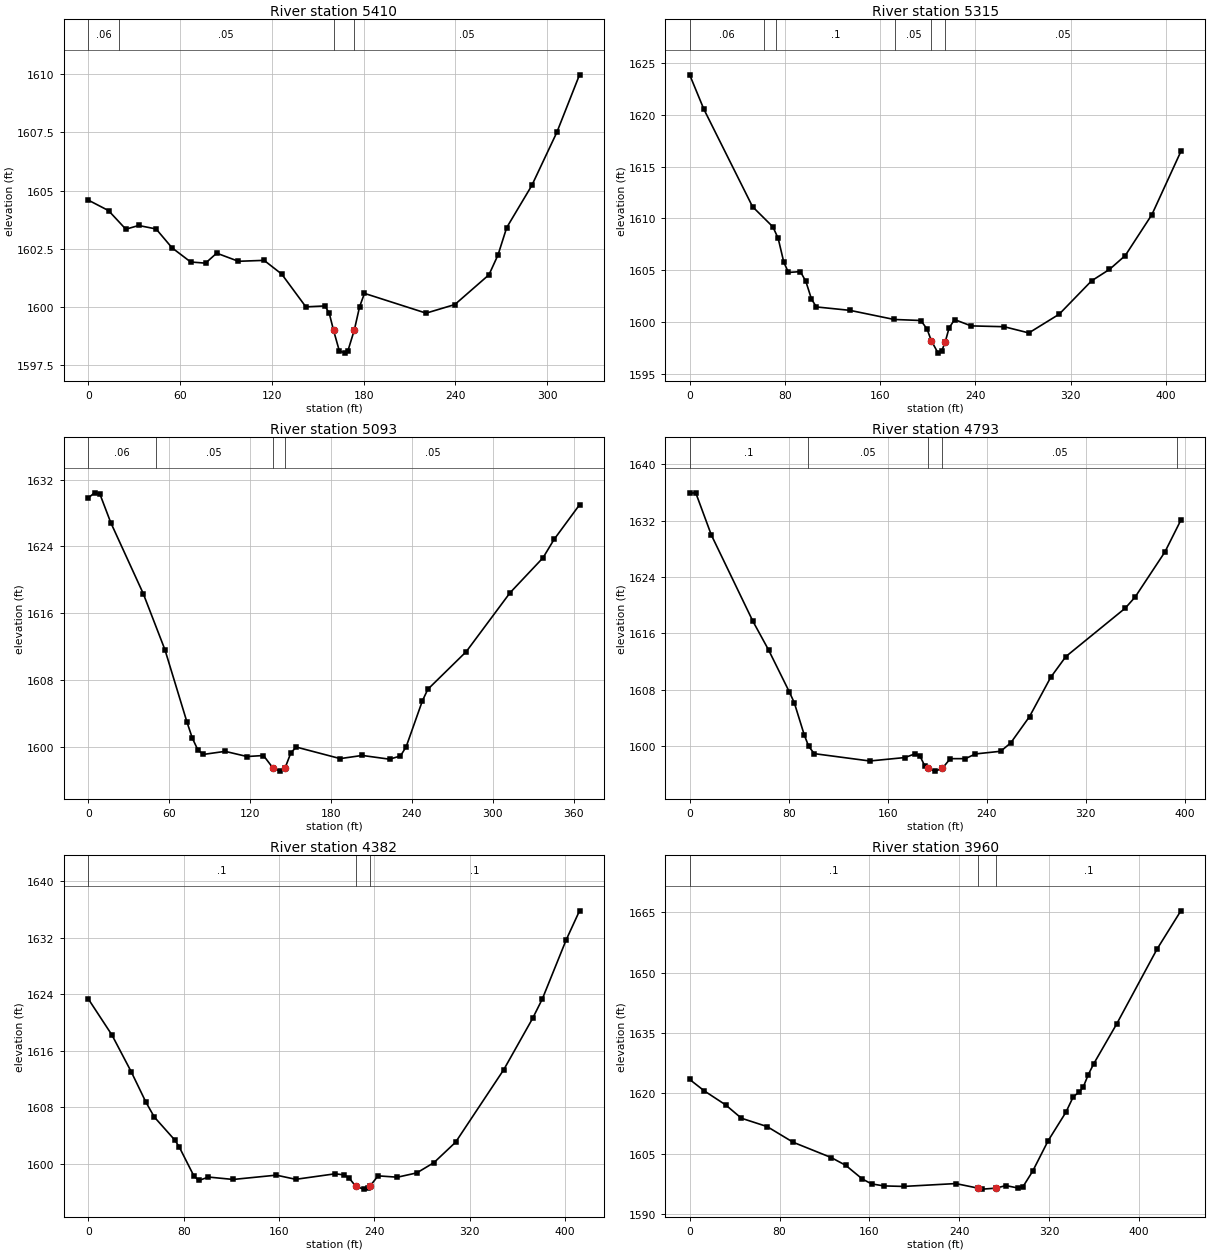
Type RM Length L Ch R = 1 ,5410    ,96.2,94.6,92.2
XS GIS Cut Line= 2
2163138.75988893666865.1468296542162919.81093573667100.019343093
#Sta/Elev= 30
       0 1604.59    13.2 1604.14    24.5 1603.34    32.9  1603.5    44.3 1603.35
    54.7 1602.54    66.9 1601.93    76.6 1601.88    83.9 1602.31    98.1 1601.96
   114.9    1602   126.4 1601.41   142.2    1600   154.7 1600.04   157.5 1599.72
   160.3 1598.99   164.1  1598.1     168 1598.01   169.6 1598.09   173.9 1599.01
   177.3    1600   180.5 1600.58   220.8 1599.73   239.6  1600.1   261.9 1601.38
   267.8 1602.23   273.5 1603.41   289.9 1605.22   306.3 1607.51   321.1 1609.98
#Mann= 4 ,-1,0
       0     .06       0      20     .05       0   160.3    .045       0
   173.9     .05       0
Bank Sta=160.3,173.9
XS Rating Curve= 0 ,0
Exp/Cntr(USF)=0,0
Exp/Cntr=0.3,0.1

Type RM Length L Ch R = 1 ,5315    ,224.6,221.9,218.2
XS GIS Cut Line= 4
2163017.98268232666740.3026001542163034.69259121666790.432326815
2162875.45698887667064.6714197292162856.78120835667103.005916587
#Sta/Elev= 30
       0 1623.86    11.9 1620.54    52.8 1611.13    69.9 1609.18    74.3 1608.08
    79.1 1605.75      83 1604.78      93 1604.86    97.6 1603.91   102.3 1602.21
   106.4 1601.45   134.6 1601.12   171.7 1600.24   194.2 1600.14   199.4 1599.31
     203 1598.18   208.7 1596.99   211.8 1597.22   214.7 1598.09   217.9 1599.42
   222.5 1600.23   236.4 1599.62   264.2 1599.54   284.9 1598.94   310.4 1600.75
   337.6 1603.97   352.6 1605.07   365.9 1606.41   388.3 1610.37   412.6 1616.46
#Mann= 6 ,-1,0
       0     .06       0   62.84     .05       0   72.84      .1       0
  172.84     .05       0     203    .045       0   214.7     .05       0
Bank Sta=203,214.7
XS Rating Curve= 0 ,0
Exp/Cntr(USF)=0,0
Exp/Cntr=0.3,0.1

Type RM Length L Ch R = 1 ,5093    ,296,300.6,295.7
XS GIS Cut Line= 4
2162771.46433037666744.5493875922162769.03732835666794.302928941
2162730.20529608667011.5196094652162713.21628196667103.745686112
#Sta/Elev= 30
       0 1629.82     4.6 1630.42     8.6 1630.26    16.6 1626.86    40.7 1618.35
    56.8 1611.62    73.1 1602.97    77.1 1601.03    81.2 1599.62    85.2 1599.07
   101.5 1599.44   117.7 1598.82   129.9 1598.94   136.71597.493   142.1 1597.07
     1461597.487   150.3  1599.3   154.3 1599.95   186.8 1598.57   203.1 1598.95
   223.4  1598.5   231.5 1598.89   235.7 1599.98   247.8 1605.51   251.8 1606.88
   280.3 1611.39   312.8 1618.45   337.2 1622.63   345.4 1624.83   364.3 1628.98
#Mann= 4 ,-1,0
       0     .06       0   49.81     .05       0   136.7    .045       0
     146     .05       0
Bank Sta=136.7,146
XS Rating Curve= 0 ,0
Exp/Cntr(USF)=0,0
Exp/Cntr=0.3,0.1

Type RM Length L Ch R = 1 ,4793    ,405.5,411,405.4
XS GIS Cut Line= 4
 2162590.6526801666704.5038543122162567.59616094666776.100413814
2162527.55062766 666990.890092322162525.12362564667094.037678043
#Sta/Elev= 30
       0 1635.91     4.9 1635.96    17.5 1629.97    51.1 1617.72    63.7 1613.67
    80.4 1607.74    84.5 1606.17    92.6 1601.58    96.2 1599.95   100.7 1598.93
   145.5 1597.89     174 1598.38   182.1 1598.91   186.2 1598.55   190.2 1597.11
   192.3 1596.83   198.4 1596.45   204.11596.835   210.6 1598.22   222.8 1598.22
   230.9 1598.89   251.3 1599.27   259.4 1600.45   274.6 1604.19   291.7 1609.76
     304 1612.72     352 1619.59     360 1621.18     384 1627.56   396.9 1632.08
#Mann= 5 ,-1,0
       0      .1       0   95.22     .05       0   192.3    .045       0
   204.1     .05       0  393.71      .1       0
Bank Sta=192.3,204.1
XS Rating Curve= 0 ,0
Exp/Cntr(USF)=0,0
Exp/Cntr=0.3,0.1

Type RM Length L Ch R = 1 ,4382    ,411.3,421.8,432.4
XS GIS Cut Line= 4
2162343.18412195666653.5952470282162334.68961489666713.056796445
2162287.36307556666976.3865152922162276.44156648667060.118084879
#Sta/Elev= 30
       0  1623.3    19.8  1618.2    35.9 1613.02    48.3 1608.69    55.3 1606.59
    72.7 1603.29    76.4 1602.29    88.6 1598.22    92.7  1597.6   100.8 1598.08
   121.5 1597.74   157.7 1598.35     174 1597.76     207 1598.54   214.6 1598.39
   218.7 1597.96   224.2  1596.8   230.9 1596.37   234.9 1596.49   236.51596.844
   243.1 1598.25   259.3 1598.06   275.6 1598.67     290 1600.13   308.1 1603.01
   348.6 1613.31   372.8 1620.57   380.9 1623.31     401 1631.71   412.1 1635.79
#Mann= 3 ,-1,0
       0      .1       0   224.2    .045       0   236.5      .1       0
Bank Sta=224.2,236.5
XS Rating Curve= 0 ,0
Exp/Cntr(USF)=0,0
Exp/Cntr=0.3,0.1

Type RM Length L Ch R = 1 ,3960    ,288.4,289.3,283.1
XS GIS Cut Line= 4
2162247.31754228666601.4147036622162144.16995656666665.730257113
2161952.43679721666764.0238388022161861.42422157  666806.4963741
#Sta/Elev= 30
       0 1623.46    13.1 1620.61      32 1617.15    46.1 1613.83    68.9 1611.77
    92.1 1607.87     126 1604.07     139 1602.13   153.8 1598.73     162 1597.52
     173 1597.02   190.5 1596.89     237  1597.6   256.61596.478   260.8 1596.22
   272.7 1596.46   281.6  1597.1   292.4  1596.5   296.9 1596.84   305.4 1600.62
   319.3 1608.25     335 1615.27   341.7 1619.18   347.1 1620.38   350.5 1621.53
     355 1624.65     360 1627.42   380.2 1637.19   416.3 1655.86   437.5 1665.36
#Mann= 3 ,-1,0
       0      .1       0   256.6    .045       0   272.7      .1       0
Bank Sta=256.6,272.7
XS Rating Curve= 0 ,0
Exp/Cntr(USF)=0,0
Exp/Cntr=0.3,0.1

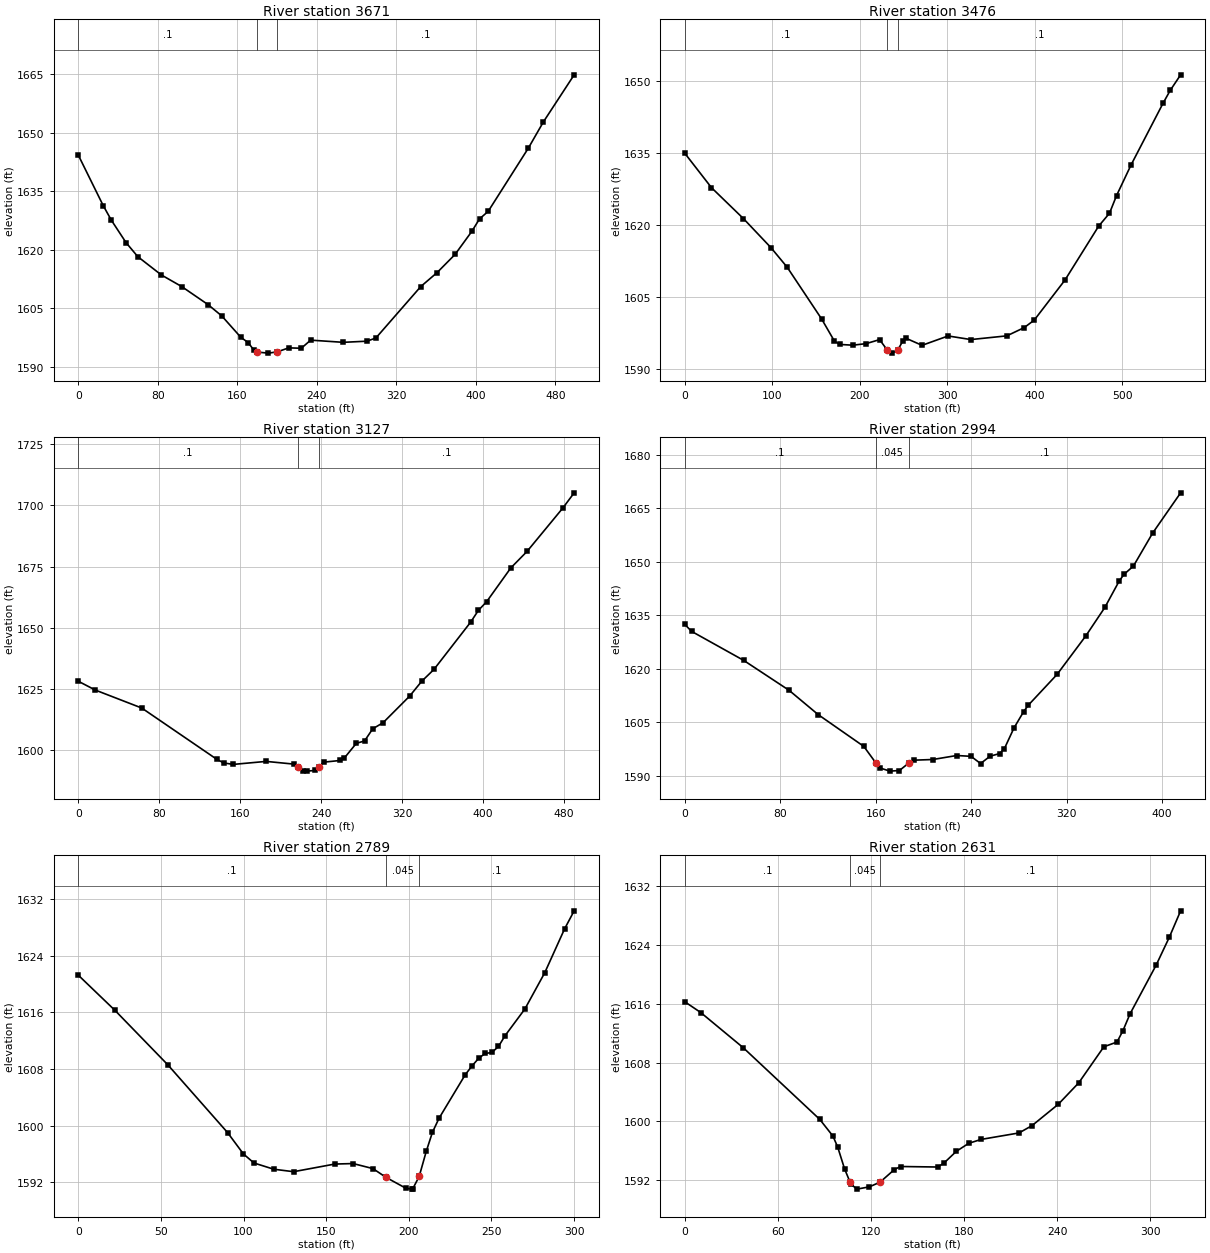
Type RM Length L Ch R = 1 ,3671    ,194.9,195,188.8
XS GIS Cut Line= 4
2162134.27523377666374.3119286432162053.37516654666417.458631168
 2161797.1916203666573.8654278212161737.86490432666662.855501778
#Sta/Elev= 30
       0  1644.3      25 1631.38    33.2 1627.63      48 1621.88    59.8 1618.28
    83.5 1613.59     104 1610.61   130.6 1605.96   144.3 1603.08   163.4 1597.62
   170.9 1596.23   176.7 1594.27   179.7 1593.81   191.3 1593.54     200 1593.86
   211.7 1594.89   224.3 1594.79   233.7 1596.87   266.5 1596.31   290.2  1596.6
   299.3 1597.41   344.5 1610.61   360.9 1614.19     379 1618.85   395.8 1624.74
   403.6 1627.96   412.3 1629.89   452.7  1646.1   467.9 1652.85   498.8  1664.9
#Mann= 3 ,-1,0
       0      .1       0   179.7    .045       0     200      .1       0
Bank Sta=179.7,200
XS Rating Curve= 0 ,0
Exp/Cntr(USF)=0,0
Exp/Cntr=0.3,0.1

Type RM Length L Ch R = 1 ,3476    ,340.8,348.8,353.2
XS GIS Cut Line= 4
2162027.75681191666219.253466445 2161919.8900556666274.535179055
2161673.14485054666467.3470059632161646.17816146666596.787113537
#Sta/Elev= 30
       0 1634.92    30.5 1627.77      67 1621.34    98.4 1615.31     117 1611.23
   156.4 1600.46     171 1595.86     177 1595.18   191.9 1595.02   207.1 1595.34
   222.6 1596.18   231.2 1594.04   236.9 1593.37   243.6 1594.07   248.9 1595.83
   252.8 1596.46   271.1 1594.99   300.9 1596.94   326.9 1596.19     368 1596.96
   387.9 1598.68   399.3 1600.23   434.4 1608.55     473 1619.79   485.3 1622.45
   493.4 1626.13   509.8 1632.44   546.5 1645.32   554.7 1647.99   566.6 1651.23
#Mann= 3 ,-1,0
       0      .1       0   231.2    .045       0   243.6      .1       0
Bank Sta=231.2,243.6
XS Rating Curve= 0 ,0
Exp/Cntr(USF)=0,0
Exp/Cntr=0.3,0.1

Type RM Length L Ch R = 1 ,3127    ,129.5,132.5,132.2
XS GIS Cut Line= 4
2161836.29331946666045.3183218912161727.07822869666077.678348785
2161514.04138498666111.3867101332161353.58958496666116.780047948
#Sta/Elev= 30
       0  1628.2    16.8  1624.6    62.7 1617.27   137.1 1596.28     144 1594.83
   153.3 1594.27   185.7 1595.49   213.1 1594.38  216.64 1593.25   222.1 1591.55
   226.2 1591.52   234.3 1591.82   238.3  1593.3   242.4 1595.17   258.6 1595.86
   262.6  1596.7   274.8 1602.87   282.9 1603.83     291 1608.79   301.3 1611.31
   327.4  1622.1   339.5 1628.23   351.5 1633.02   387.7 1652.28   395.5 1657.16
   403.5 1660.62   427.5 1674.46   443.5 1681.18   478.8 1698.84   490.1  1705.1
#Mann= 3 ,-1,0
       0      .1       0  216.64    .045       0   238.3      .1       0
Bank Sta=216.64,238.3
XS Rating Curve= 0 ,0
Exp/Cntr(USF)=0,0
Exp/Cntr=0.3,0.1

Type RM Length L Ch R = 1 ,2994    ,207.1,205.1,203.5
XS GIS Cut Line= 4
2161825.77097764665960.5286647052161717.84462495665982.644720586
2161527.64654438665984.414005056 2161412.6430538665987.952573997
#Sta/Elev= 30
       0 1632.48     5.7 1630.53    49.3  1622.4    87.4 1613.99   111.8 1607.17
     150 1598.26   159.8 1593.75   163.8 1592.19   171.8 1591.33   179.8  1591.5
   187.8 1593.64   191.8  1594.4   207.8 1594.59   227.8 1595.71   239.8 1595.48
   247.8 1593.46   255.8 1595.52   263.8 1596.26   267.8 1597.67   275.8 1603.45
   283.8 1607.97   287.8 1609.83   311.9 1618.46   335.9 1629.23   351.9 1637.23
   363.9 1644.63   367.9  1646.5   375.9 1648.87   391.9 1658.07   415.4 1669.39
#Mann= 3 ,-1,0
       0      .1       0   159.8    .045       0   187.8      .1       0
Bank Sta=159.8,187.8
XS Rating Curve= 0 ,0
Exp/Cntr(USF)=0,0
Exp/Cntr=0.3,0.1

Type RM Length L Ch R = 1 ,2789    ,159.9,158.4,157.9
XS GIS Cut Line= 3
 2161766.2798489665807.6215275272161699.04703902665803.198316351
2161466.38613116665805.852243056
#Sta/Elev= 30
       0 1621.23    22.2 1616.26    54.2 1608.57    90.3 1599.02    99.9    1596
   106.3 1594.72   118.3 1593.84   130.3 1593.49   155.2 1594.57   166.3 1594.64
   178.3 1593.93   186.3 1592.68   198.3 1591.15   201.8 1591.03   202.3 1591.03
   206.3 1592.82   210.6 1596.38   214.3 1599.04   218.3 1601.03   234.2 1607.19
   238.2  1608.4   242.3  1609.5   246.2 1610.18   250.3 1610.32   254.3 1611.17
   258.3  1612.7   270.3 1616.47   282.3 1621.58   294.3 1627.77   300.1 1630.32
#Mann= 3 ,-1,0
       0      .1       0   186.3    .045       0   206.3      .1       0
Bank Sta=186.3,206.3
XS Rating Curve= 0 ,0
Exp/Cntr(USF)=0,0
Exp/Cntr=0.3,0.1

Type RM Length L Ch R = 1 ,2631    ,259.6,254.3,245.3
XS GIS Cut Line= 4
2161749.43643992 665648.175734832161696.04239554665673.659256009
2161547.99527251665670.0187529832161441.20718376 665705.21028223
#Sta/Elev= 30
       0 1616.27    10.3  1614.8    37.7 1610.01      87 1600.26    95.5 1597.99
    98.6 1596.48     103 1593.53   106.4 1591.79     107 1591.46     111 1590.76
     119 1591.07   125.9 1591.71   135.1 1593.42   139.1 1593.84   163.1 1593.77
   167.1 1594.31   175.1 1595.91   183.1    1597   191.1 1597.53   215.5 1598.41
   223.9 1599.41   240.8 1602.31     254 1605.23   270.2 1610.14   278.7 1610.79
   282.5 1612.33   287.1 1614.63   303.9 1621.25   312.4 1625.05   319.7 1628.65
#Mann= 3 ,-1,0
       0      .1       0   106.4    .045       0   125.9      .1       0
Bank Sta=106.4,125.9
XS Rating Curve= 0 ,0
Exp/Cntr(USF)=0,0
Exp/Cntr=0.3,0.1

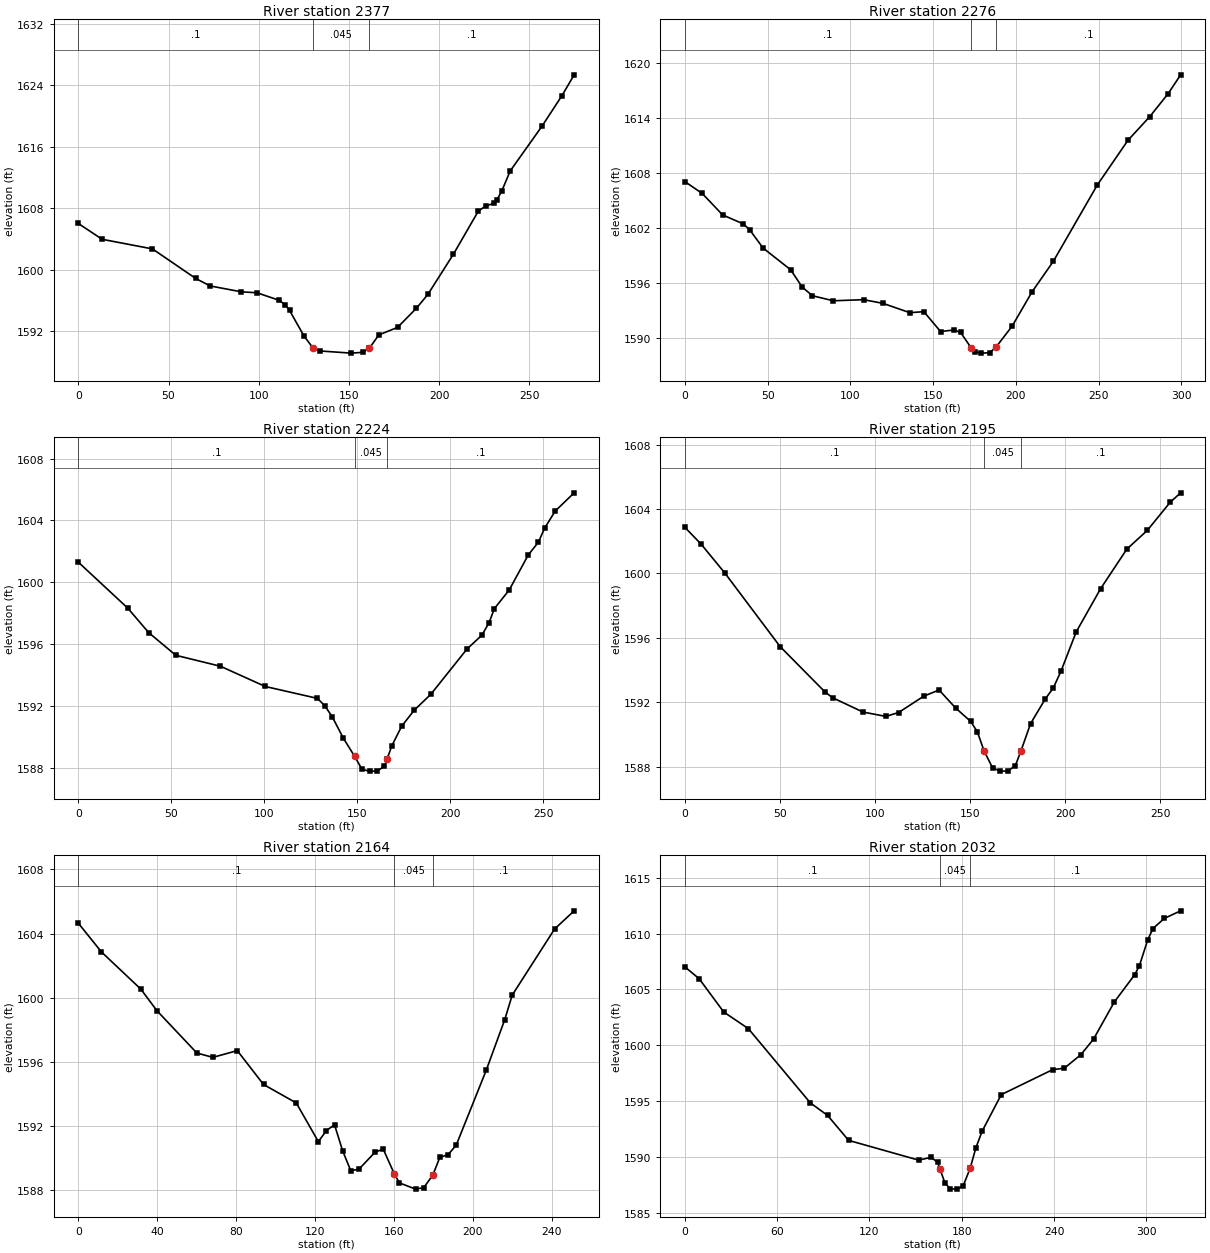
Type RM Length L Ch R = 1 ,2377    ,97.8,101,105.4
XS GIS Cut Line= 5
2161609.26534827665485.1820913152161551.84406642665484.873433446
2161518.99637374665486.2971272962161425.71576472665563.359295341
2161368.01743226665590.095149561
#Sta/Elev= 30
       0 1606.03    13.2 1603.97    41.1 1602.72    65.1 1598.87    73.1  1597.9
    90.3 1597.14    99.1 1597.01   111.4 1596.03   114.7 1595.45   117.1 1594.72
   125.1 1591.39   130.3 1589.78   134.1 1589.44   151.2 1589.16   157.6 1589.26
   161.4 1589.81   166.6 1591.53     177 1592.51   187.4 1594.99   193.8  1596.8
     208 1602.05   221.8 1607.65   225.9 1608.31   230.6 1608.66   231.9 1609.04
   234.7 1610.21   239.4 1612.85   257.1  1618.7   268.1 1622.65   274.9 1625.37
#Mann= 3 ,-1,0
       0      .1       0   130.3    .045       0   161.4      .1       0
Bank Sta=130.3,161.4
XS Rating Curve= 0 ,0
Exp/Cntr(USF)=0,0
Exp/Cntr=0.3,0.1

Type RM Length L Ch R = 1 ,2276    ,47.5,51.6,55.4
XS GIS Cut Line= 4
2161586.48745565665386.0119384142161531.63359755665397.366730952
2161366.81033187665460.9614037522161300.77665943665471.030345687
#Sta/Elev= 30
       0 1607.08    10.5 1605.78    22.8 1603.44    35.4 1602.44    39.1 1601.83
    47.3 1599.81      64 1597.43    70.9 1595.55    77.1  1594.6    89.7 1594.05
     108 1594.17   119.7 1593.77   135.9 1592.75   144.4 1592.86   154.5 1590.69
   162.6 1590.86   166.6 1590.59     173  1588.9   175.5 1588.48   179.2 1588.33
   184.1 1588.37     188 1588.99   197.8  1591.3   209.8 1595.04   222.6 1598.36
   249.2 1606.71   267.7 1611.59   280.8 1614.16     292 1616.69   299.5 1618.74
#Mann= 3 ,-1,0
       0      .1       0     173    .045       0     188      .1       0
Bank Sta=173,188
XS Rating Curve= 0 ,0
Exp/Cntr(USF)=0,0
Exp/Cntr=0.3,0.1

Type RM Length L Ch R = 1 ,2224    ,29.2,29.2,29.3
XS GIS Cut Line= 5
2161550.76527013665378.9767045532161503.17134095665392.326221274
2161430.03920586665394.647876356 2161329.0472098665396.969531438
2161291.32031472665376.655049471
#Sta/Elev= 30
       0  1601.3    26.6 1598.32    37.8 1596.74    52.4 1595.27    76.4 1594.56
   100.5 1593.25   128.5 1592.48   132.5    1592   136.5 1591.28   142.5 1589.89
   148.5 1588.73   152.5 1587.88   156.5 1587.77   160.5 1587.77   164.5 1588.08
     166 1588.57   168.5 1589.41   173.8 1590.68   180.5 1591.71   189.5 1592.75
     209 1595.69   216.9 1596.57   220.8 1597.39   223.6 1598.29   231.6  1599.5
   241.8 1601.76   247.3  1602.6   250.7 1603.52   256.4 1604.62   266.5 1605.79
#Mann= 3 ,-1,0
       0      .1       0   148.5    .045       0     166      .1       0
Bank Sta=148.5,166
XS Rating Curve= 0 ,0
Exp/Cntr(USF)=0,0
Exp/Cntr=0.3,0.1

Type RM Length L Ch R = 1 ,2195    ,32.3,30.6,28.6
XS GIS Cut Line= 5
2161548.40962125665354.9149221412161515.32603633 665364.78195624
2161470.05376223665367.1036113222161338.29983633665370.005680174
2161295.34921731665346.208715584
#Sta/Elev= 30
       0 1602.87     8.6 1601.82    21.1 1600.02    50.1 1595.46    73.7 1592.64
    77.7 1592.28    93.7 1591.39   105.7 1591.12   112.4 1591.36   125.7 1592.38
   133.7 1592.76   142.4 1591.64   150.3 1590.81   153.8 1590.17   157.4 1588.96
   161.8 1587.93   165.8 1587.72   169.8 1587.72   173.8 1588.06  176.79 1588.99
   181.8 1590.67   189.4 1592.18   193.8  1592.9   197.8 1593.93   205.8 1596.37
   218.6 1599.05   232.4 1601.51   243.2 1602.68   255.2 1604.42   260.7 1605.01
#Mann= 3 ,-1,0
       0      .1       0   157.4    .045       0  176.79      .1       0
Bank Sta=157.4,176.79
XS Rating Curve= 0 ,0
Exp/Cntr(USF)=0,0
Exp/Cntr=0.3,0.1

Type RM Length L Ch R = 1 ,2164    ,132.5,132,131.3
XS GIS Cut Line= 4
2161535.71553873665308.6402860682161469.35530457665317.987238996
 2161320.5054373665353.3719083962161290.73448653665343.303905614
#Sta/Elev= 30
       0 1604.65    11.7 1602.86    31.7 1600.54    39.9 1599.19    60.1 1596.56
    68.2 1596.29    80.6 1596.71    93.9  1594.6   110.5 1593.45   121.7 1591.04
   125.8 1591.73   129.9 1592.09     134 1590.47   138.1 1589.24   142.2 1589.31
   150.5 1590.39   154.6 1590.57   160.3 1589.01   162.8 1588.47     171 1588.08
   175.1 1588.17   179.71588.945   183.3 1590.06   187.5 1590.23   191.6 1590.82
   206.8 1595.48   216.2 1598.64     220 1600.17   241.5 1604.29   251.4 1605.42
#Mann= 3 ,-1,0
       0      .1       0   160.3    .045       0   179.7      .1       0
Bank Sta=160.3,179.7
XS Rating Curve= 0 ,0
Exp/Cntr(USF)=0,0
Exp/Cntr=0.3,0.1

Type RM Length L Ch R = 1 ,2032    ,87.7,87.3,86.4
XS GIS Cut Line= 4
2161489.41721549665192.0727977012161416.90185625665196.046242043
2161280.81138753665231.8072411222161200.34913961 665305.31596145
#Sta/Elev= 30
       0 1607.03     9.3 1605.97    25.3 1602.98    41.3 1601.49    81.6 1594.83
    92.8 1593.71   106.5 1591.47     152  1589.7   160.2 1589.95   164.4 1589.49
   165.9 1588.89   169.1 1587.65   172.6 1587.13   176.8  1587.1   180.9 1587.38
   185.5 1588.97   189.2  1590.8   193.3  1592.3   205.7 1595.57   239.1 1597.81
   246.7 1597.94   257.5 1599.16   265.7 1600.55   279.2 1603.88   292.5 1606.33
   295.5 1607.13   300.9 1609.44   304.3 1610.46   311.7 1611.37   322.3 1612.05
#Mann= 3 ,-1,0
       0      .1       0   165.9    .045       0   185.5      .1       0
Bank Sta=165.9,185.5
XS Rating Curve= 0 ,0
Exp/Cntr(USF)=0,0
Exp/Cntr=0.3,0.1

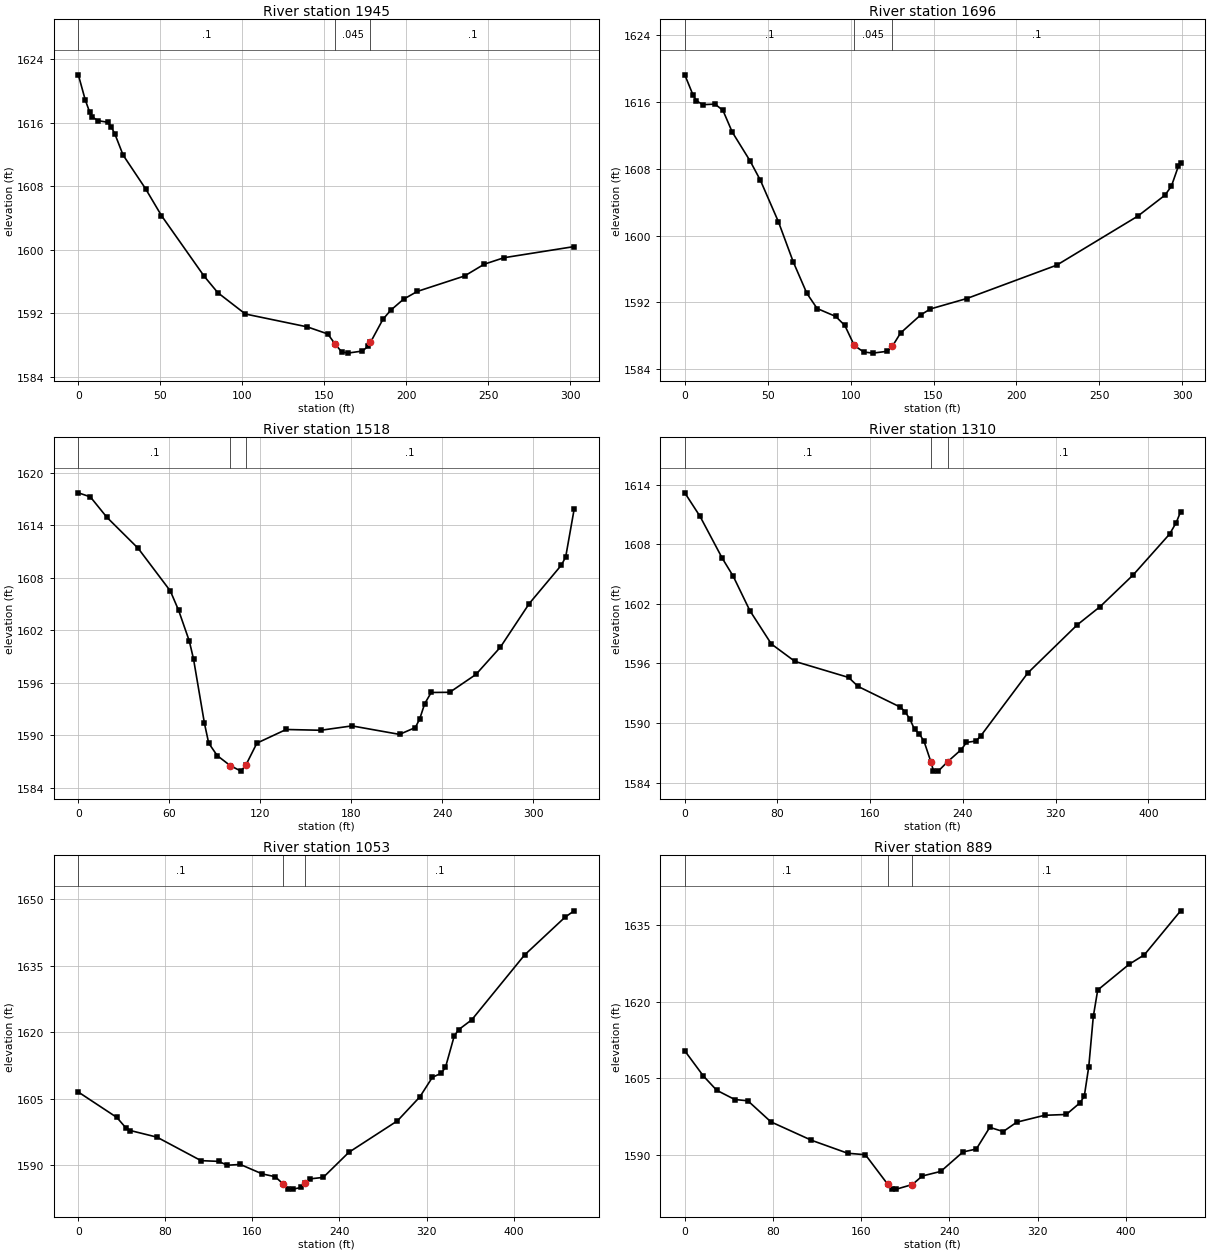
Type RM Length L Ch R = 1 ,1945    ,252.3,248.5,239.8
XS GIS Cut Line= 4
 2161447.4685715665075.0452809272161392.42416576665107.482162884
2161240.06911414665155.6460179122161161.43424879665149.748403011
#Sta/Elev= 30
       0 1622.01     4.2 1618.87     6.9 1617.32     8.5  1616.7    12.1 1616.24
    17.8 1616.05      20  1615.5    22.4 1614.52    27.3 1611.92      41 1607.69
    50.7 1604.31    76.7  1596.7    85.1 1594.61   101.9 1591.93   139.7 1590.31
   152.2 1589.42   156.4 1588.22   160.6 1587.18   164.3 1587.01   173.2 1587.27
     177 1587.89   178.2 1588.35   185.8 1591.25   190.5 1592.39   198.4 1593.79
   206.8 1594.77   235.6 1596.71   247.6 1598.19   259.7 1599.01   302.5 1600.41
#Mann= 3 ,-1,0
       0      .1       0   156.4    .045       0   178.2      .1       0
Bank Sta=156.4,178.2
XS Rating Curve= 0 ,0
Exp/Cntr(USF)=0,0
Exp/Cntr=0.3,0.1

Type RM Length L Ch R = 1 ,1696    ,179.1,178.7,182.5
XS GIS Cut Line= 3
2161251.70793715664868.1999890222161111.14811533665011.708618289
2161014.82040527 665030.38439881
#Sta/Elev= 30
       0 1619.27       5 1616.83       7 1616.17    10.8 1615.69    18.2 1615.76
      23 1615.01    28.6 1612.41    39.3 1608.97    45.6 1606.62    56.5 1601.63
    65.4 1596.84    73.6 1593.07    79.8 1591.25      91  1590.3    96.5 1589.22
   102.2 1586.82   107.8 1586.04   113.4  1585.9     122 1586.12   125.1  1586.7
   130.1 1588.31   142.2 1590.47     148 1591.19   170.1 1592.45   224.3 1596.45
   273.2 1602.33   289.5 1604.83   293.4  1605.9   297.6 1608.29     299 1608.72
#Mann= 3 ,-1,0
       0      .1       0   102.2    .045       0   125.1      .1       0
Bank Sta=102.2,125.1
XS Rating Curve= 0 ,0
Exp/Cntr(USF)=0,0
Exp/Cntr=0.3,0.1

Type RM Length L Ch R = 1 ,1518    ,213.8,208.2,199.6
XS GIS Cut Line= 4
2161183.92359106664755.0355592242161122.61788416664766.182051388
2160987.26762218664880.0355070582160928.35044931664945.322104017
#Sta/Elev= 30
       0  1617.7     7.9 1617.24    18.8 1614.91    39.5 1611.35    60.7 1606.48
    66.2 1604.25    73.2 1600.76      76  1598.7    83.2 1591.35      86 1589.09
    91.6 1587.67   100.2 1586.52   107.3 1585.89   110.5 1586.57   117.8 1589.09
   137.1 1590.65   159.9 1590.56   180.5 1591.06   211.9 1590.09   222.3 1590.87
   225.2 1591.85   228.5  1593.6   232.8 1594.88     245  1594.9   262.3 1596.94
   278.4 1600.05   297.5 1605.05   318.6 1609.42   321.5 1610.36   327.1 1615.83
#Mann= 3 ,-1,0
       0      .1       0   100.2    .045       0   110.5      .1       0
Bank Sta=100.2,110.5
XS Rating Curve= 0 ,0
Exp/Cntr(USF)=0,0
Exp/Cntr=0.3,0.1

Type RM Length L Ch R = 1 ,1310    ,237.5,256.6,271.3
XS GIS Cut Line= 4
2161023.18874269664576.7767933162160926.10866201 664640.14851265
 2160888.3552973664843.7470151892160804.75856116664907.118734523
#Sta/Elev= 30
       0 1613.18    13.2  1610.8    32.3  1606.6    41.8 1604.78    56.1 1601.33
    74.7 1597.96      95 1596.21   141.4 1594.59   149.5 1593.69   186.1  1591.6
   190.2 1591.13   194.3 1590.38   198.3 1589.36   202.4 1588.92   206.5 1588.15
   212.5 1586.05   214.6 1585.19   218.7 1585.16   226.91586.115   238.6 1587.33
   243.1 1588.05   251.2 1588.19   255.3 1588.69     296 1595.04   338.6 1599.88
   358.5 1601.73     387 1604.92   418.4 1609.03   424.1 1610.18   427.9 1611.28
#Mann= 3 ,-1,0
       0      .1       0   212.5    .045       0   226.9      .1       0
Bank Sta=212.5,226.9
XS Rating Curve= 0 ,0
Exp/Cntr(USF)=0,0
Exp/Cntr=0.3,0.1

Type RM Length L Ch R = 1 ,1053    ,163.7,164.1,164.1
XS GIS Cut Line= 4
2160978.69370571664564.6417832312160889.70363175 664584.86680004
2160641.61009224664567.3384521392160527.00166365664551.158438692
#Sta/Elev= 30
       0 1606.47    35.4 1600.73    43.6  1598.4    47.7 1597.78    72.3 1596.28
   112.8 1590.97   128.9 1590.81   136.9 1589.94   148.9 1590.11     169 1587.98
     181 1587.34   188.2  1585.7     193 1584.68   197.1 1584.54   205.1 1584.92
   208.5  1585.9   213.1 1586.86   225.1 1587.19   248.6 1592.85   293.3 1599.97
   313.9 1605.38   325.4  1609.8   333.4  1610.7   337.4 1612.02   345.5 1619.14
   349.5 1620.55   361.6 1622.79   410.1 1637.42   447.3 1645.96   455.7  1647.4
#Mann= 3 ,-1,0
       0      .1       0   188.2    .045       0   208.5      .1       0
Bank Sta=188.2,208.5
XS Rating Curve= 0 ,0
Exp/Cntr(USF)=0,0
Exp/Cntr=0.3,0.1

Type RM Length L Ch R = 1 ,889     ,129.5,133.3,133
XS GIS Cut Line= 4
2161016.45056405664456.946214634 2160872.6282223664425.485077376
2160752.77627084664412.0017328382160574.49649305  664376.0461474
#Sta/Elev= 30
       0 1610.38    16.8 1605.49    28.9  1602.7    45.3 1600.89    57.2 1600.64
    78.1 1596.53   114.9 1592.94   147.7 1590.41   163.8 1590.12   184.1 1584.34
   187.9 1583.47     192 1583.41   206.4 1584.31   215.4 1585.97   232.2 1586.87
   252.3 1590.66   264.4 1591.23   276.6 1595.46   288.8 1594.64   301.1 1596.47
   326.3 1597.81     346 1597.97   358.2  1600.2   362.3  1601.5   366.4 1607.32
   370.5 1617.08   374.5 1622.24   403.1 1627.28   416.8 1629.11   449.7 1637.69
#Mann= 3 ,-1,0
       0      .1       0   184.1    .045       0   206.4      .1       0
Bank Sta=184.1,206.4
XS Rating Curve= 0 ,0
Exp/Cntr(USF)=0,0
Exp/Cntr=0.3,0.1

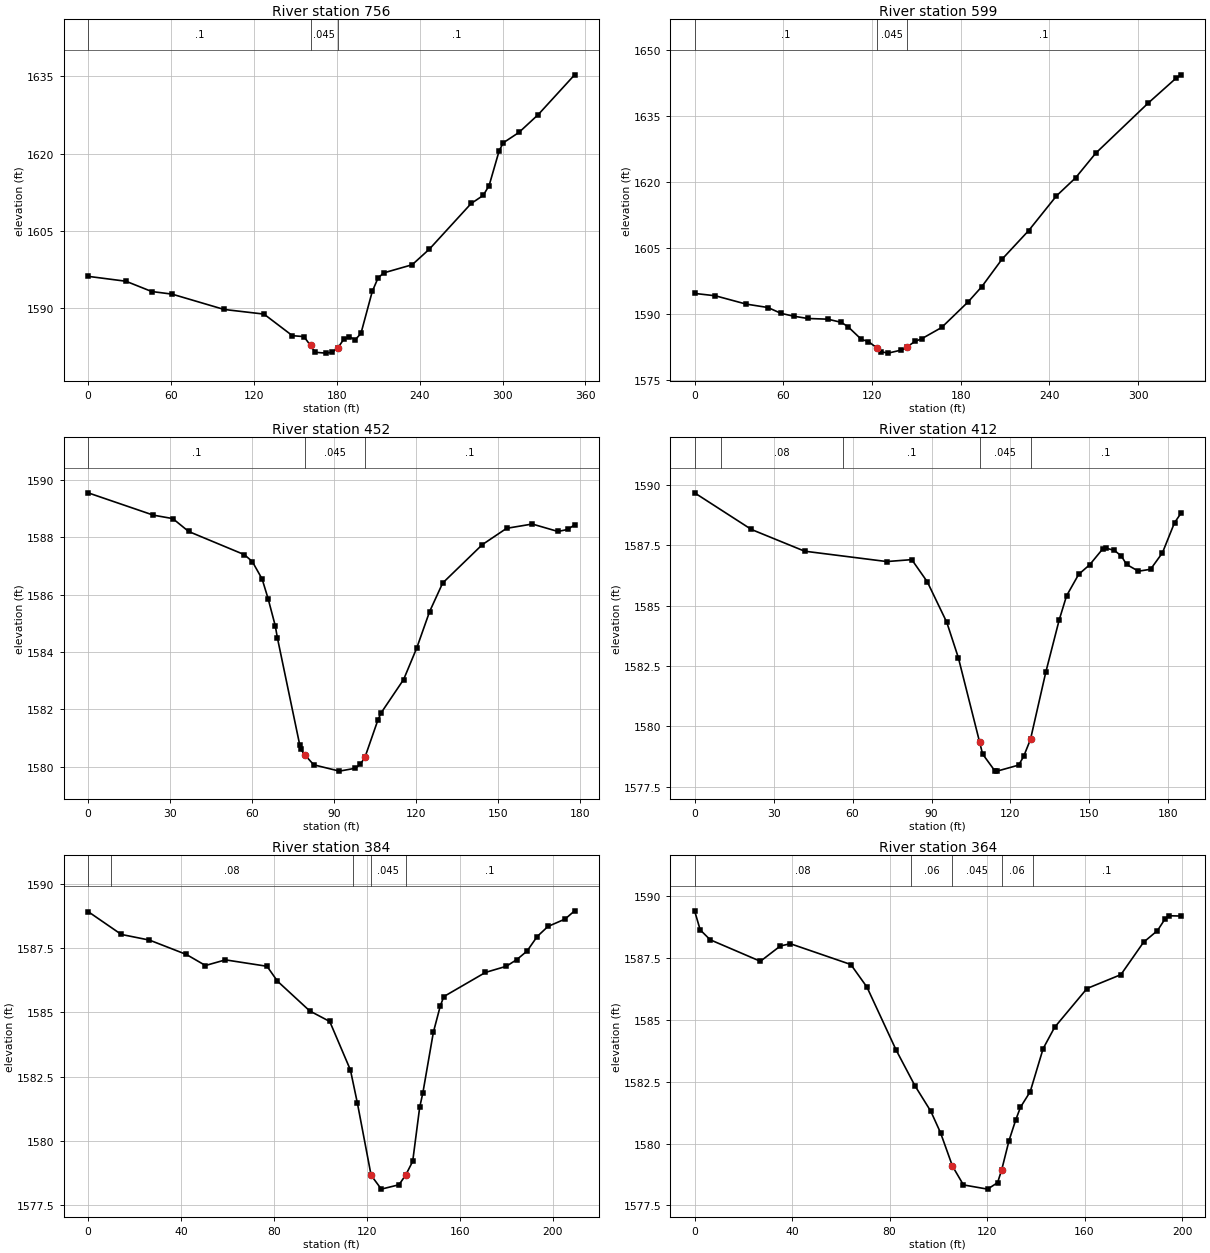
Type RM Length L Ch R = 1 ,756     ,152.2,156.1,159.5
XS GIS Cut Line= 4
2160986.48757618664340.0905619632160890.60601502664311.625723491
2160749.77997205664275.670138054 2160650.9021121664235.220104437
#Sta/Elev= 30
       0 1596.21    27.4 1595.26      46 1593.27    60.8 1592.76    98.4 1589.79
   127.3 1588.89   147.9  1584.7   156.2 1584.53     161  1582.8   164.5 1581.48
   172.1 1581.32   176.8  1581.5     181 1582.41   185.1 1584.02   189.2 1584.49
   193.3  1583.9   197.5 1585.13   205.7 1593.28   209.9  1595.9     214 1596.88
   234.6 1598.46   247.1  1601.5   277.3 1610.34     286  1611.9   290.3 1613.82
   297.6 1620.59   300.6 1622.12   311.9 1624.12   325.9 1627.59   352.2 1635.29
#Mann= 3 ,-1,0
       0      .1       0     161    .045       0     181      .1       0
Bank Sta=161,181
XS Rating Curve= 0 ,0
Exp/Cntr(USF)=0,0
Exp/Cntr=0.3,0.1

Type RM Length L Ch R = 1 ,599     ,141.5,147.5,154.3
XS GIS Cut Line= 2
2161023.76404462664228.6156894452160733.12306233664074.306301943
#Sta/Elev= 30
       0 1594.64    14.1  1594.1    34.8 1592.22    49.6 1591.44    58.4 1590.12
      67 1589.47    76.5 1588.95    90.1 1588.79    99.2 1588.07   103.7 1587.11
   112.8 1584.21   117.6  1583.7   123.5 1582.22   126.3 1581.39   130.9 1581.08
   139.9 1581.78   143.8  1582.5     149 1583.73   153.5 1584.32   167.1  1586.9
   185.2 1592.77   194.3 1596.18   207.9 1602.38     226 1608.91   244.8 1616.79
   257.7 1620.88   271.4  1626.5   306.9 1637.88   325.6 1643.49   329.1 1644.28
#Mann= 3 ,-1,0
       0      .1       0   123.5    .045       0   143.8      .1       0
Bank Sta=123.5,143.8
XS Rating Curve= 0 ,0
Exp/Cntr(USF)=0,0
Exp/Cntr=0.3,0.1

Type RM Length L Ch R = 1 ,452     ,39.3,40,39.9
XS GIS Cut Line= 2
2161044.76293636664127.3318428542160950.81393098663976.058020633
#Sta/Elev= 30
       0 1589.56    23.9 1588.78      31 1588.66    36.8 1588.21    57.2  1587.4
    60.1 1587.16    63.7 1586.55    65.9 1585.86    68.5 1584.92    69.3 1584.49
    77.5 1580.74    77.9  1580.6    79.4  1580.4    82.6 1580.06      92 1579.84
    97.8 1579.94    99.7 1580.08   101.4 1580.34   106.1 1581.63   107.3 1581.88
   115.5 1583.04   120.3 1584.14     125 1585.41   129.8 1586.41   144.3 1587.75
   153.2 1588.32   162.6 1588.47     172 1588.21   175.5 1588.28   178.1 1588.44
#Mann= 3 ,-1,0
       0      .1       0    79.4    .045       0   101.4      .1       0
Bank Sta=79.4,101.4
XS Rating Curve= 0 ,0
Exp/Cntr(USF)=0,0
Exp/Cntr=0.3,0.1

Type RM Length L Ch R = 1 ,412     ,27.5,27.8,28.1
XS GIS Cut Line= 3
2161067.99124425664134.5486620842161061.64441967664088.428403467
2160995.63744403663966.992493162
#Sta/Elev= 30
       0 1589.68    21.6 1588.16    41.8 1587.26      73 1586.83    82.5 1586.91
    88.4 1585.99    95.8 1584.31   100.2 1582.84   108.3 1579.33   109.4 1578.85
     114 1578.16   114.9 1578.14   123.1 1578.39     125 1578.75   127.6 1579.46
   133.4 1582.24   138.5 1584.41   141.3 1585.41   145.9  1586.3   150.1  1586.7
     155 1587.35   156.2 1587.39   159.5 1587.29   162.1 1587.06   164.1 1586.71
   168.6 1586.43   173.2 1586.51   177.7 1587.19   182.3 1588.44   184.8 1588.84
#Mann= 5 ,-1,0
       0     .07       0      10     .08       0   56.55      .1       0
   108.3    .045       0   127.6      .1       0
Bank Sta=108.3,127.6
XS Rating Curve= 0 ,0
Exp/Cntr(USF)=0,0
Exp/Cntr=0.3,0.1

Type RM Length L Ch R = 1 ,384     ,21.7,20.6,19.6
XS GIS Cut Line= 3
2161092.53229929664135.3949053612161086.75115883664081.655918733
2161016.88323497663942.868531593
#Sta/Elev= 30
       0 1588.93    14.3 1588.04    26.4 1587.82    42.3 1587.26    50.5 1586.83
    59.1 1587.05      77  1586.8    81.5 1586.22    95.4 1585.06     104 1584.65
   112.9 1582.76   115.9 1581.47   121.8 1578.66   126.2 1578.12   133.8 1578.29
   136.7 1578.67   139.7  1579.2   142.7  1581.3   144.1 1581.88   148.6 1584.23
   151.6 1585.26   153.1 1585.62     171 1586.56     180  1586.8   184.5 1587.06
   188.9 1587.39   193.3 1587.96   197.9 1588.35   205.3 1588.64   209.4 1588.96
#Mann= 5 ,-1,0
       0     .07       0      10     .08       0  114.05      .1       0
   121.8    .045       0   136.7      .1       0
Bank Sta=121.8,136.7
XS Rating Curve= 0 ,0
Exp/Cntr(USF)=0,0
Exp/Cntr=0.3,0.1

Type RM Length L Ch R = 1 ,364     ,37.6,36,34.5
XS GIS Cut Line= 3
2161111.81502618664111.3912044782161095.46340337664044.622078017
2161027.33164168663932.885988836
#Sta/Elev= 30
       0 1589.41     2.3 1588.64     6.4 1588.24      27 1587.37    35.2 1587.99
    39.3 1588.08    64.1 1587.24    70.7 1586.33    82.7 1583.78    90.4 1582.34
    96.9 1581.31   100.9 1580.44   105.8 1579.09   110.3 1578.33   120.2 1578.16
   124.3 1578.42     126 1578.94     129 1580.12   131.8 1580.97   133.7 1581.47
   137.7  1582.1     143 1583.84   147.7  1584.7     161 1586.27   174.9 1586.83
   184.2 1588.14   189.9 1588.61     193 1589.08   194.6 1589.21   199.6  1589.2
#Mann= 5 ,-1,0
       0     .08       0   88.74     .06       0   105.8    .045       0
     126     .06       0  138.74      .1       0
Bank Sta=105.8,126
XS Rating Curve= 0 ,0
Exp/Cntr(USF)=0,0
Exp/Cntr=0.3,0.1

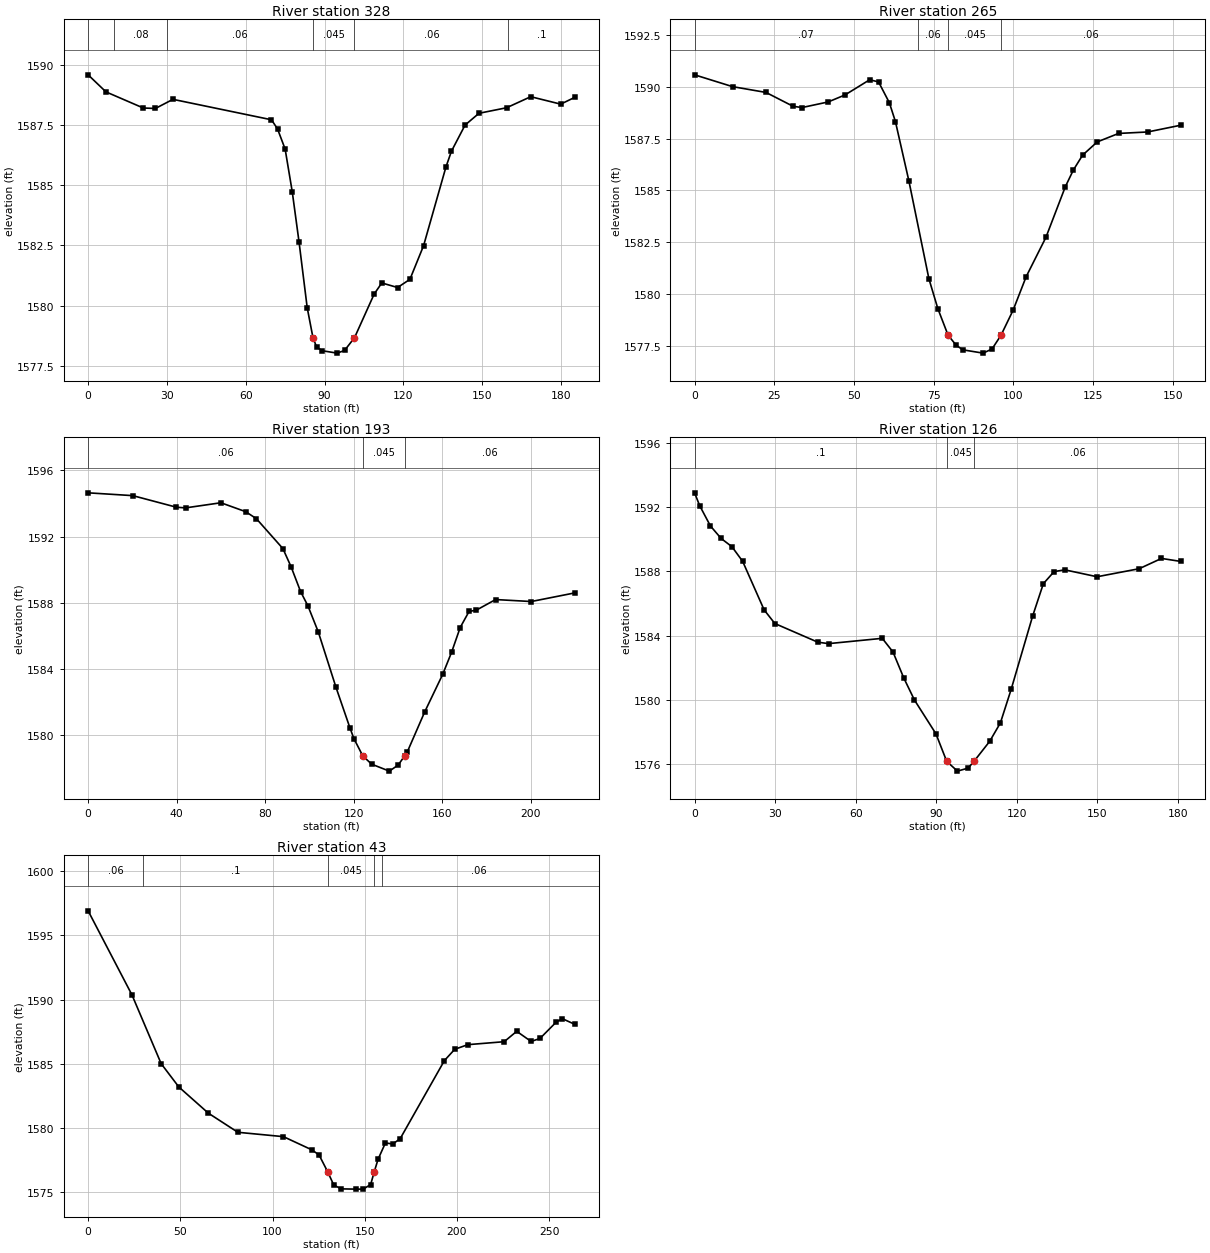
Type RM Length L Ch R = 1 ,328     ,62.2,62.3,62.2
XS GIS Cut Line= 2
2161160.84185705 664054.120825812161040.24477363663913.531712512
#Sta/Elev= 30
       0  1589.6     6.8 1588.89      21 1588.22    25.6  1588.2    32.3 1588.58
    69.8 1587.73    72.1 1587.35      75 1586.51    77.7 1584.74    80.3 1582.64
    83.4 1579.91    85.6 1578.66      87 1578.27    89.1 1578.12    94.8 1578.02
    97.6 1578.13   101.4 1578.66   108.9 1580.48   111.8 1580.94   117.8 1580.75
   122.5 1581.09   127.7 1582.49   136.2 1585.76   138.3 1586.42   143.5 1587.51
   148.8    1588   159.3 1588.23   168.5 1588.69   179.9 1588.38   185.2 1588.66
#Mann= 6 ,-1,0
       0      .1       0      10     .08       0      30     .06       0
    85.6    .045       0   101.4     .06       0     160      .1       0
Bank Sta=85.6,101.4
XS Rating Curve= 0 ,0
Exp/Cntr(USF)=0,0
Exp/Cntr=0.3,0.1

Type RM Length L Ch R = 1 ,265     ,80.6,72.3,63.4
XS GIS Cut Line= 2
2161203.95170796664008.9738392382161104.56043503663893.207758886
#Sta/Elev= 30
       0 1590.58    11.9 1590.01    22.4 1589.73    30.9 1589.06    33.7    1589
    41.9 1589.27    47.2 1589.61    54.9 1590.34    57.7 1590.24    61.1 1589.23
      63 1588.32    67.2 1585.47    73.5 1580.73    76.3 1579.29    79.5 1578.01
      82 1577.53    84.1  1577.3    90.5 1577.14    93.3 1577.34    96.1    1578
    99.9 1579.21     104 1580.83   110.2 1582.73   116.3 1585.18   118.8 1585.98
   121.7  1586.7   126.3 1587.34     133 1587.75   142.1 1587.82   152.6 1588.15
#Mann= 4 ,-1,0
       0     .07       0      70     .06       0    79.5    .045       0
    96.1     .06       0
Bank Sta=79.5,96.1
XS Rating Curve= 0 ,0
Exp/Cntr(USF)=0,0
Exp/Cntr=0.3,0.1

Type RM Length L Ch R = 1 ,193     ,66.5,67.3,67.9
XS GIS Cut Line= 3
2161299.87016657663870.6564453542161277.29851994663873.880966302
2161080.60274216663884.199433333
#Sta/Elev= 30
       0 1594.65    20.2 1594.48    39.9 1593.78      44 1593.74      60 1594.05
    71.2 1593.51      76 1593.09      88 1591.28    91.7 1590.18      96 1588.68
    99.3 1587.82     104 1586.24     112 1582.89   118.3 1580.44   120.1 1579.79
   124.1 1578.75   128.1 1578.25   136.1 1577.83   140.1  1578.2   143.1 1578.77
   144.1 1578.96   152.1 1581.42   160.2 1583.68   164.2 1585.01   168.1 1586.51
   172.1 1587.48   175.4 1587.56   184.1  1588.2   200.2 1588.08   219.8  1588.6
#Mann= 3 ,-1,0
       0     .06       0   124.1    .045       0   143.1     .06       0
Bank Sta=124.1,143.1
XS Rating Curve= 0 ,0
Exp/Cntr(USF)=0,0
Exp/Cntr=0.3,0.1

Type RM Length L Ch R = 1 ,126     ,82.5,82.5,82.5
XS GIS Cut Line= 2
2161254.08196912663816.4844934422161072.86389189663813.259972494
#Sta/Elev= 30
       0 1592.88     1.9 1592.08     5.9 1590.82     9.9 1590.04    13.9 1589.53
    17.9 1588.62    25.9  1585.6    29.9 1584.75    45.9 1583.59    49.9  1583.5
    69.9 1583.83    73.9 1582.98    77.9 1581.37    81.9 1579.99    89.9 1577.89
    93.9 1576.18    97.9 1575.57   101.9 1575.76   104.21576.208   109.9 1577.42
   113.9 1578.57   117.9 1580.65   125.9 1585.21   129.9 1587.23   133.9 1587.98
   137.9 1588.09   149.9 1587.66   165.6 1588.16   173.9  1588.8   181.2 1588.61
#Mann= 3 ,-1,0
       0      .1       0    93.9    .045       0   104.2     .06       0
Bank Sta=93.9,104.2
XS Rating Curve= 0 ,0
Exp/Cntr(USF)=0,0
Exp/Cntr=0.3,0.1

Type RM Length L Ch R = 1 ,43      ,,,
XS GIS Cut Line= 6
2161307.53097174663754.5281813272161273.76506226663733.867361925
2161124.87977408663733.8673619252161115.32563794663743.421498065
2161092.23647561663760.1412363092161064.61706038 663778.70014576
#Sta/Elev= 30
       0 1596.92    23.8 1590.36    39.6 1585.01    49.2 1583.19    65.2 1581.15
    81.2 1579.66   105.9 1579.32   121.2  1578.3   125.2  1577.9   129.9 1576.58
   133.2 1575.55   137.2 1575.25   145.2 1575.23   149.2 1575.23   153.2 1575.59
  155.15 1576.58   157.2 1577.55   161.2 1578.83   165.2 1578.75   169.2 1579.16
   193.2 1585.25   198.8 1586.13   205.9 1586.49   225.6 1586.72   232.4 1587.53
   240.2 1586.74     245 1586.97   253.9 1588.26   257.2 1588.51   263.8 1588.08
#Mann= 5 ,-1,0
       0     .06       0      30      .1       0   129.9    .045       0
  155.15      .1       0  159.59     .06       0
Bank Sta=129.9,155.15
XS Rating Curve= 0 ,0
Exp/Cntr(USF)=0,0
Exp/Cntr=0.3,0.1
LCMann Table=0

Chan Stop Cuts=-1
Use User Specified Reach Order=0
Composite Channel Slope=5